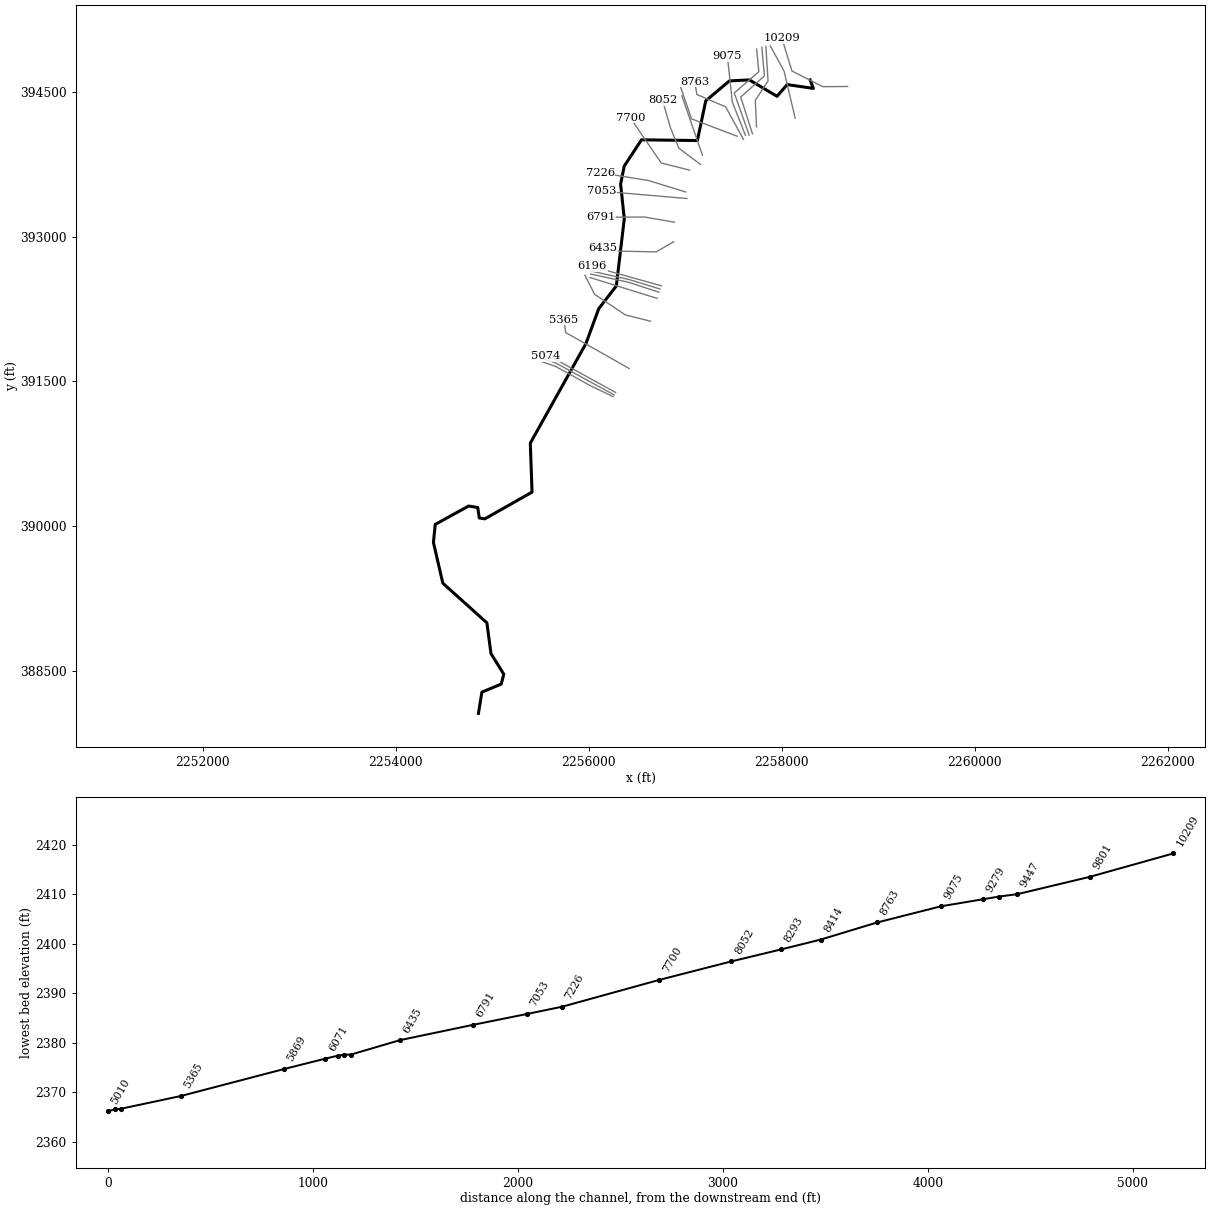
--- ANTHNYCK.prj (project) ---

Proj Title=ANTHNYCK
Current Plan=p01
Default Exp/Contr=0,0
English Units
Geom File=g01
Flow File=f01
Plan File=p01
Background Map Layer=Inundation Boundary (0_2pct Value_0)
Background Map Layer=Inundation Boundary (01pct Value_0)
BEGIN DESCRIPTION:
----------MODEL BY WOOD PLC 2021----------
Stream Name: Anthony Creek
Flood Zone: Enhanced Approximate
Pocahontas County, WV
HEC-RAS Version: RAS 6.1
Vertical Datum: NAVD88
Projection: NAD 1983 StatePlane West Virginia S FIPS 4702 (US Feet)
Terrain: 1-meter LIDAR (FEMA Region III 3DEP collected 2016-2018)
Land Use: 2019 NLCD
Hydrologic Method:
WV SIR2010-5033 regression equations
END DESCRIPTION:
DSS File=dss
DSS Export Rating Curves= 0
DSS Export Rating Curve Sorted= 0
DSS Export Volume Flow Curves= 0
DXF OffsetX= 0
DXF OffsetY= 0
DXF ScaleX= 0
DXF ScaleY= 0

--- ANTHNYCK.p01 (plan) ---

Plan Title=Floodplain
Program Version=6.10
Short Identifier=Floodplain
Geom File=g01
Flow File=f01
Subcritical Flow
K Sum by GR= 0
Std Step Tol= 0.01
Critical Tol= 0.01
Num of Std Step Trials= 20
Max Error Tol= 0.3
Flow Tol Ratio= 0.001
Split Flow NTrial= 30
Split Flow Tol= 0.02
Split Flow Ratio= 0.02
Log Output Level= 0
Friction Slope Method= 1
Unsteady Friction Slope Method= 2
Unsteady Bridges Friction Slope Method= 1
Parabolic Critical Depth
Global Vel Dist= 0 , 0 , 0
Global Log Level= 0
CheckData=True
Encroach Param=-1 ,0,0, 0
Computation Interval=0.1SEC
Output Interval=1SEC
Instantaneous Interval=Max Profile
Mapping Interval=1HOUR
Computation Time Step Use Courant=        0
Computation Time Step Use Time Series=    0
Computation Time Step Count To Double=0
Computation Time Step Max Doubling=0
Computation Time Step Max Halving=0
Computation Time Step Residence Courant=0
Run HTab= 0
Run UNet= 0
Run Sediment= 0
Run PostProcess= 0
Run WQNet= 0
Run RASMapper= 0
UNET Theta= 0
UNET Theta Warmup= 0
UNET ZTol= 0
UNET ZSATol= 0
UNET MxIter= 0
UNET Max Iter WO Improvement= 0
UNET MaxInSteps= 0
UNET DtIC= 0
UNET DtMin= 0
UNET MaxCRTS= 0
UNET WFStab= 0
UNET SFStab= 0
UNET WFX= 1
UNET SFX= 1
UNET Gravity=32.174
UNET 1D Methodology=Finite Difference
UNET DSS MLevel= 1
UNET Pardiso=0
UNET DZMax Abort= 0
UNET Use Existing IB Tables= 0
UNET Froude Reduction=False
UNET Froude Limit= 0
UNET Froude Power= 0
UNET D1 Cores= 0
UNET WindReference=Eulerian
UNET WindDragFormulation=Hsu (1988)
UNET D2 Coriolis=0
UNET D2 Cores= 0
UNET D2 Theta= 1
UNET D2 Theta Warmup= 1
UNET D2 Z Tol= 0.01
UNET D2 Volume Tol= 0.01
UNET D2 Max Iterations= 20
UNET D2 Equation= 0
UNET D2 RampUpFraction=0.1
UNET D2 TimeSlices= 1
UNET D2 Turbulence Formulation=Non-Conservative (original)
UNET D2 Eddy Viscosity=0.3
UNET D2 Transverse Eddy Viscosity=0.3
UNET D2 Smagorinsky Mixing=0
UNET D2 BCVolumeCheck=0
UNET D2 Cores=0
UNET D2 SolverType=PARDISO (Direct)
UNET D2 Minimum Iterations= 2147483647
UNET D2 Maximum Iterations= 2147483647
UNET D2 Restart Number= 10
UNET D2 Relaxation Coeff=1.3
UNET D2 SOR Precondition Iterations= 10
UNET D2 ILUT Maximum Fill= 8
UNET D2 ILUT Tolerance=1E-08
UNET D1D2 MaxIter= 0
UNET D1D2 ZTol=0.01
UNET D1D2 QTol=0.1
UNET D1D2 MinQTol=1
DSS File=dss
Write IC File= 0
Write IC File at Fixed DateTime=0
Write IC File at Sim End=0
Echo Input=False
Echo Parameters=False
Echo Output=False
Write Detailed= 0
HDF Write Warmup=0
HDF Write Time Slices=0
HDF Flush=0
HDF Compression= 1
HDF Chunk Size= 1
HDF Spatial Parts= 1
HDF Use Max Rows=0
HDF Fixed Rows= 1
Calibration Method= 0
Calibration Iterations= 20
Calibration Max Change=0.05
Calibration Tolerance=0.2
Calibration Maximum=1.5
Calibration Minimum=0.5
Calibration Optimization Method= 1
WQ AD Non Conservative
WQ ULTIMATE=-1
WQ Max Comp Step=1HOUR
WQ Output Interval=15MIN
WQ Output Selected Increments= 0
WQ Output face flow=0
WQ Output face velocity=0
WQ Output face area=0
WQ Output face dispersion=0
WQ Output cell volume=0
WQ Output cell surface area=0
WQ Output cell continuity=0
WQ Output cumulative cell continuity=0
WQ Output face conc=0
WQ Output face dconc_dx=0
WQ Output face courant=0
WQ Output face peclet=0
WQ Output face adv mass=0
WQ Output face disp mass=0
WQ Output cell mass=0
WQ Output cell source sink temp=0
WQ Output nsm pathways=0
WQ Output nsm derived pathways=0
WQ Create Restart=0
WQ Fixed Restart=0
WQ System Summary=0
WQ Write To DSS=0
Sorting and Armoring Iterations= 10
XS Update Threshold= 0.02
Bed Roughness Predictor= 0
Hydraulics Update Threshold= 0.02
Energy Slope Method= 1
Volume Change Method= 1
Sediment Retention Method= 0
Sediment TS Multiplier= 1
Warm Up Method= 0
XS Weighting Method= 0
Number of US Weighted Cross Sections= 1
Number of DS Weighted Cross Sections= 1
Upstream XS Weight=0
Main XS Weight=1
Downstream XS Weight=0
Number of DS XS's Weighted with US Boundary= 1
Upstream Boundary Weight= 1
Weight of XSs Associated with US Boundary= 0
Number of US XS's Weighted with DS Boundary= 1
Downstream Boundary Weight= 0.5
Weight of XSs Associated with DS Boundary= 0.5
Percentile Method= 0
Sediment Output Level= 3
Mass or Volume Output= 0
Output Increment Type= 1
Profile and TS Output Increment= 1
Transport Output Increment 1
XS Output Flag= 0
XS Output Increment= 10
Read HDF5 Sediment Hotstart= 0
Sediment Hotstart Type= 0
Write Gradation File= 0
Read Gradation Hotstart= 0
Write HDF5 File= 1
Write Binary Output= 1
Write DSS Sediment File= 0
DSS Sediment Output Type= 1
SV Curve= 0
Specific Gage Flag= 0
Subcell Erosion Methods= 0
Subcell Deposition Methods= 0
Advection Scheme= 1
Matrix Solver= 0
Implicit Weighting Factor= 1
Maximum Outer Loop Convergence Iterations= 5
Convergence Maximum Absolute= 0.001
Convergence RMSE= 0.0001
Grain Fractions Max Abs Error= 0.001
Max Subgrid Regions= 1
Max Subgrid Length Scale= 3.402823E+38
Initial Layer Thickness= 3.402823E+38
Min Layer Thickness= 3.402823E+38
Max Layer Thickness= 3.402823E+38
Number of Layers= 5

--- ANTHNYCK.f01 (steady flow) ---

Flow Title=Flow
Program Version=6.00
Number of Profiles= 6
Profile Names=01pct,10pct,04pct,02pct,0_2pct,01plus
River Rch & RM=ANTHNYCK,Main            ,10209
     709     378     501     601     987    1050
River Rch & RM=ANTHNYCK,Main            ,8414
     806     432     575     685    1120    1190
River Rch & RM=ANTHNYCK,Main            ,7226
     909     489     644     772    1260    1340
River Rch & RM=ANTHNYCK,Main            ,3358
    1060     573     754     902    1460    1570
River Rch & RM=ANTHNYCK,Main            ,2678
    1310     714     935    1120    1800    1930
Boundary for River Rch & Prof#=ANTHNYCK,Main            , 1
Up Type= 0
Dn Type= 1
Dn Known WS=2334.3
Boundary for River Rch & Prof#=ANTHNYCK,Main            , 2
Up Type= 0
Dn Type= 1
Dn Known WS=2333.1
Boundary for River Rch & Prof#=ANTHNYCK,Main            , 3
Up Type= 0
Dn Type= 1
Dn Known WS=2333.6
Boundary for River Rch & Prof#=ANTHNYCK,Main            , 4
Up Type= 0
Dn Type= 1
Dn Known WS=2333.9
Boundary for River Rch & Prof#=ANTHNYCK,Main            , 5
Up Type= 0
Dn Type= 1
Dn Known WS=2335.1
Boundary for River Rch & Prof#=ANTHNYCK,Main            , 6
Up Type= 0
Dn Type= 1
Dn Known WS=2335.3
DSS Import GetInterval= 0
DSS Import GetPeak= 0
DSS Import FillOption= 0

--- ANTHNYCK.g01 (geometry) ---

Geom Title=Geometry
Program Version=6.10

River Reach=ANTHNYCK        ,Main
Reach XY= 30
     2258295.195      394626.533     2258329.019      394538.633
     2258057.469       394578.27     2257952.318      394456.744
     2257666.481      394626.504     2257459.061      394616.418
     2257213.973      394409.918     2257126.733      393997.975
     2256547.914      394005.665     2256368.862      393732.273
     2256331.698      393546.372     2256369.867      393187.068
     2256287.188      392489.858     2256105.174      392255.374
     2255972.313      391892.983     2255395.974      390860.447
     2255413.858      390352.491     2254924.773      390075.548
2254867.06446553390084.581494396     2254851.294      390193.019
2254756.50075458390208.278754576     2254410.871390017.837037675
     2254392.185      389831.237     2254489.554      389408.432
     2254946.217      388997.413     2254988.493      388678.082
     2255121.255      388464.539     2255094.852      388362.531
2254894.20744867388278.295222033      2254858.48      388058.511

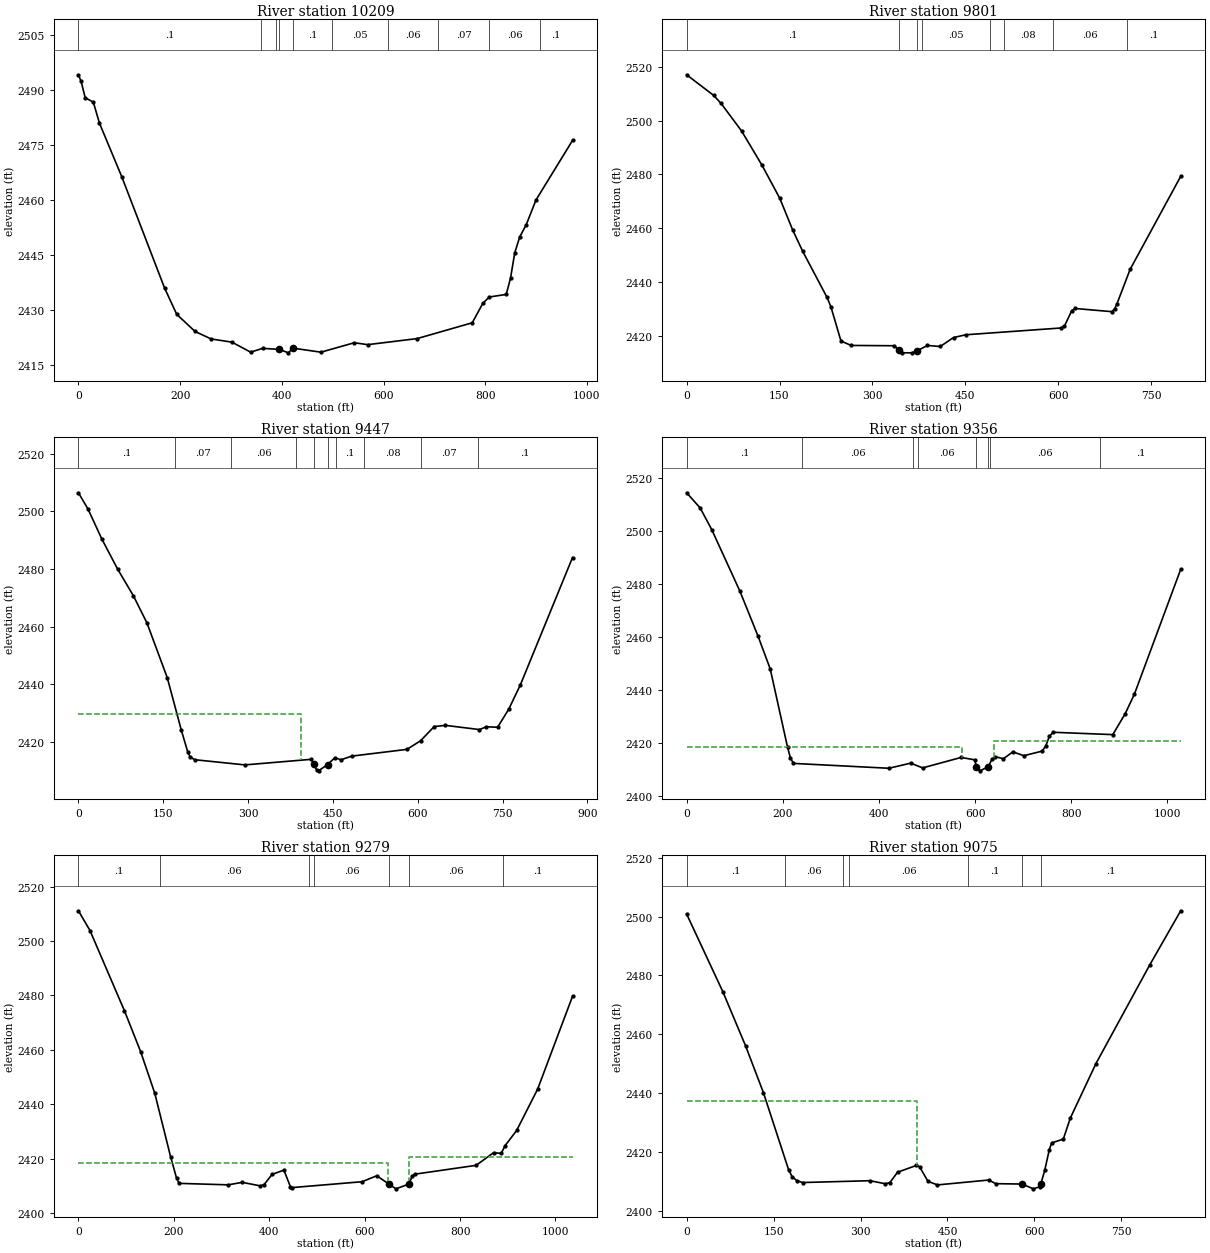
Type RM Length L Ch R = 1 ,10209   ,408,408,408
XS GIS Cut Line= 4
 2258685.4316933      394558.6412258426.01903094394556.541419665
2258106.70758185 394719.46721302     2258003.071      395057.778
#Sta/Elev= 30
       0 2494.05     5.3 2492.24    13.3 2487.81    29.3 2486.59    41.3 2480.88
    85.3 2466.25   169.3 2435.99   193.3  2428.8   229.3 2424.13   260.8 2422.09
   301.9 2421.21   338.6 2418.49   362.4 2419.52   395.1 2419.24   412.9  2418.3
   421.8 2419.58     477 2418.48   542.5 2421.05   568.9 2420.53   666.1 2422.18
   774.5 2426.49   795.4  2431.8   807.9 2433.51   841.4 2434.22   849.8 2438.68
   858.1 2445.56   867.9 2449.89   880.7 2453.21   899.9 2459.95   971.7 2476.16
#Mann= 10 ,-1,0
       0      .1       0  359.42     .05       0  389.42      .1       0
   395.1    .045       0   421.8      .1       0  499.42     .05       0
  609.42     .06       0   707.9     .07       0   807.9     .06       0
   907.9      .1       0
Bank Sta=395.1,421.8
XS Rating Curve= 0 ,0
Exp/Cntr=0.3,0.1

Type RM Length L Ch R = 1 ,9801    ,367.4,353.4,327.8
XS GIS Cut Line= 3
2258140.32343347394230.5719567882258024.87229416394719.019084643
2257882.77858424394978.784148094
#Sta/Elev= 30
       0 2517.03    43.8 2509.33    55.5 2506.41    88.7 2496.14   121.9 2483.31
   150.6    2471   171.2 2459.32   187.6 2451.28   226.7 2434.22   232.9 2430.79
   249.3 2417.96   265.7 2416.31   335.6  2416.2  342.48 2414.48   347.9 2413.59
   363.9 2413.56   372.6 2414.34     389 2416.31   409.6 2415.92   431.1 2419.26
   451.1 2420.29   604.7 2422.81   610.1 2423.47   621.9 2429.17   627.5 2430.06
   686.8 2428.88   691.3 2429.94   695.1 2431.84   716.2 2444.59     798 2479.24
#Mann= 8 ,-1,0
       0      .1       0  342.48    .045       0   372.6      .1       0
     380     .05       0     490     .06       0  511.91     .08       0
  591.91     .06       0  711.91      .1       0
Bank Sta=342.48,372.6
XS Rating Curve= 0 ,0
Exp/Cntr(USF)=0,0
Exp/Cntr=0.3,0.1

Type RM Length L Ch R = 1 ,9447    ,96.2,91,84.8
XS GIS Cut Line= 4
2257739.92578308394140.100854162 2257727.4871175 394414.93613158
2257859.42582019394616.1759710252257836.76967932394973.343368187
#Sta/Elev= 30
       0 2506.43    17.1 2500.73    41.1 2490.51    69.1 2480.05    97.2 2470.73
   121.2  2461.3   157.2 2442.26   181.7  2424.3   193.3 2416.61   197.3 2414.93
   205.3 2413.92   294.4 2412.12   411.7 2414.05   416.5 2412.32   421.3 2410.21
   424.6 2410.06   440.4 2412.23   453.5  2414.6   464.3  2413.9   483.5 2415.17
   580.9  2417.5   604.9 2420.48   629.1 2425.41     649 2425.82   709.1 2424.36
   721.2 2425.33   741.2 2425.17     761 2431.48   781.3  2439.8 873.637 2483.99
#Mann= 10 ,-1,0
       0      .1       0     170     .07       0     270     .06       0
  385.12     .05       0   416.5    .045       0   440.4     .05       0
  455.12      .1       0  505.12     .08       0  605.75     .07       0
  705.75      .1       0
#XS Ineff= 2 , 0
          392.87 2429.85
Permanent Ineff=
       F       F
Bank Sta=416.5,440.4
XS Rating Curve= 0 ,0
Exp/Cntr(USF)=0,0
Exp/Cntr=0.5,0.3

Type RM Length L Ch R = 1 ,9356    ,82.7,77.5,74.5
XS GIS Cut Line= 4
2257697.75100246394067.5774266962257575.83490684394448.849709026
2257821.31677821394668.4208089652257794.87897867 394965.14815153
#Sta/Elev= 30
       0 2514.28      28  2508.6    52.1 2500.45   110.9 2477.19   148.7  2460.2
   173.9 2447.91   209.9 2418.43   215.7  2414.5   222.1 2412.36   420.6 2410.53
   465.9 2412.45   490.8 2410.67   570.7  2414.6   598.8 2413.72   602.82411.057
     610 2409.56   627.4 2411.12   634.8 2413.88   642.2 2414.87   658.8 2414.12
   678.4 2416.71   701.3 2415.27   738.8 2416.96   746.5 2418.76   754.5 2422.65
   762.5 2424.08   886.3  2423.2   912.1  2431.1   931.2 2438.44  1027.5 2485.45
#Mann= 8 ,-1,0
       0      .1       0     240     .06       0  470.29     .07       0
  480.29     .06       0   602.8    .045       0   627.4     .05       0
  630.29     .06       0  859.64      .1       0
#XS Ineff= 2 , 0
           571.7  2418.6  638.61          2420.7
Permanent Ineff=
       F       F
Bank Sta=602.8,627.4
XS Rating Curve= 0 ,0
Exp/Cntr=0.5,0.3

Type RM Length L Ch R = 1 ,9279    ,176.3,203.4,232
XS GIS Cut Line= 4
2257663.79404196394054.3663151462257509.19919842394491.496562418
 2257763.7476046394711.2571306642257741.09146374394945.952093882
#Sta/Elev= 30
       0  2511.1    24.2 2503.85    96.3 2474.46   130.4 2459.39     160 2444.12
   193.1 2420.87   205.6    2413   210.9 2411.03   313.8 2410.49   343.5  2411.4
   381.2 2410.11   389.1 2410.56     406 2414.33   430.7  2415.9   444.2 2409.87
   448.5 2409.49   594.6 2411.63   625.4 2413.82   651.3 2410.72   665.5 2409.02
   692.7 2410.77   699.5  2413.6     705  2414.4   833.7 2417.65   870.2 2422.29
   886.3 2422.04   894.3 2424.85   918.6 2430.45   962.6 2445.621035.736  2479.7
#Mann= 7 ,-1,0
       0      .1       0     170     .06       0  483.66      .1       0
  493.66     .06       0   651.3    .045       0   692.7     .06       0
  889.95      .1       0
#XS Ineff= 2 , 0
           648.5  2418.6   693.8          2420.7
Permanent Ineff=
       F       F
Bank Sta=651.3,692.7
XS Rating Curve= 0 ,0
Exp/Cntr(USF)=0,0
Exp/Cntr=0.5,0.3

Type RM Length L Ch R = 1 ,9075    ,281.6,312.1,336.2
XS GIS Cut Line= 3
2257625.72241642394050.8327706932257488.31574655394400.111743113
2257438.01447036394874.592721767
#Sta/Elev= 30
       0 2500.87    62.7  2474.4   101.7 2456.13   132.6  2440.2   175.8 2414.17
   181.9 2411.77     190 2410.41   200.2 2409.75   316.3 2410.37   342.9 2409.33
   350.7 2409.72   363.9 2413.25   396.5 2415.55   401.9 2415.09   416.4 2410.17
   432.7 2408.94   521.2  2410.6   533.3 2409.37   578.9 2409.23   598.3 2407.61
   609.2 2408.33  611.18 2409.28   617.8 2413.84   625.8 2420.94   629.8  2423.2
   649.9 2424.48     662 2431.61   706.2  2450.1   799.3 2483.68852.4749 2501.96
#Mann= 7 ,-1,0
       0      .1       0     170     .06       0     270     .07       0
     280     .06       0  485.34      .1       0   578.9    .045       0
  611.18      .1       0
#XS Ineff= 2 , 0
           398.3 2437.35
Permanent Ineff=
       F       F
Bank Sta=578.9,611.18
XS Rating Curve= 0 ,0
Exp/Cntr(USF)=0,0
Exp/Cntr=0.3,0.1

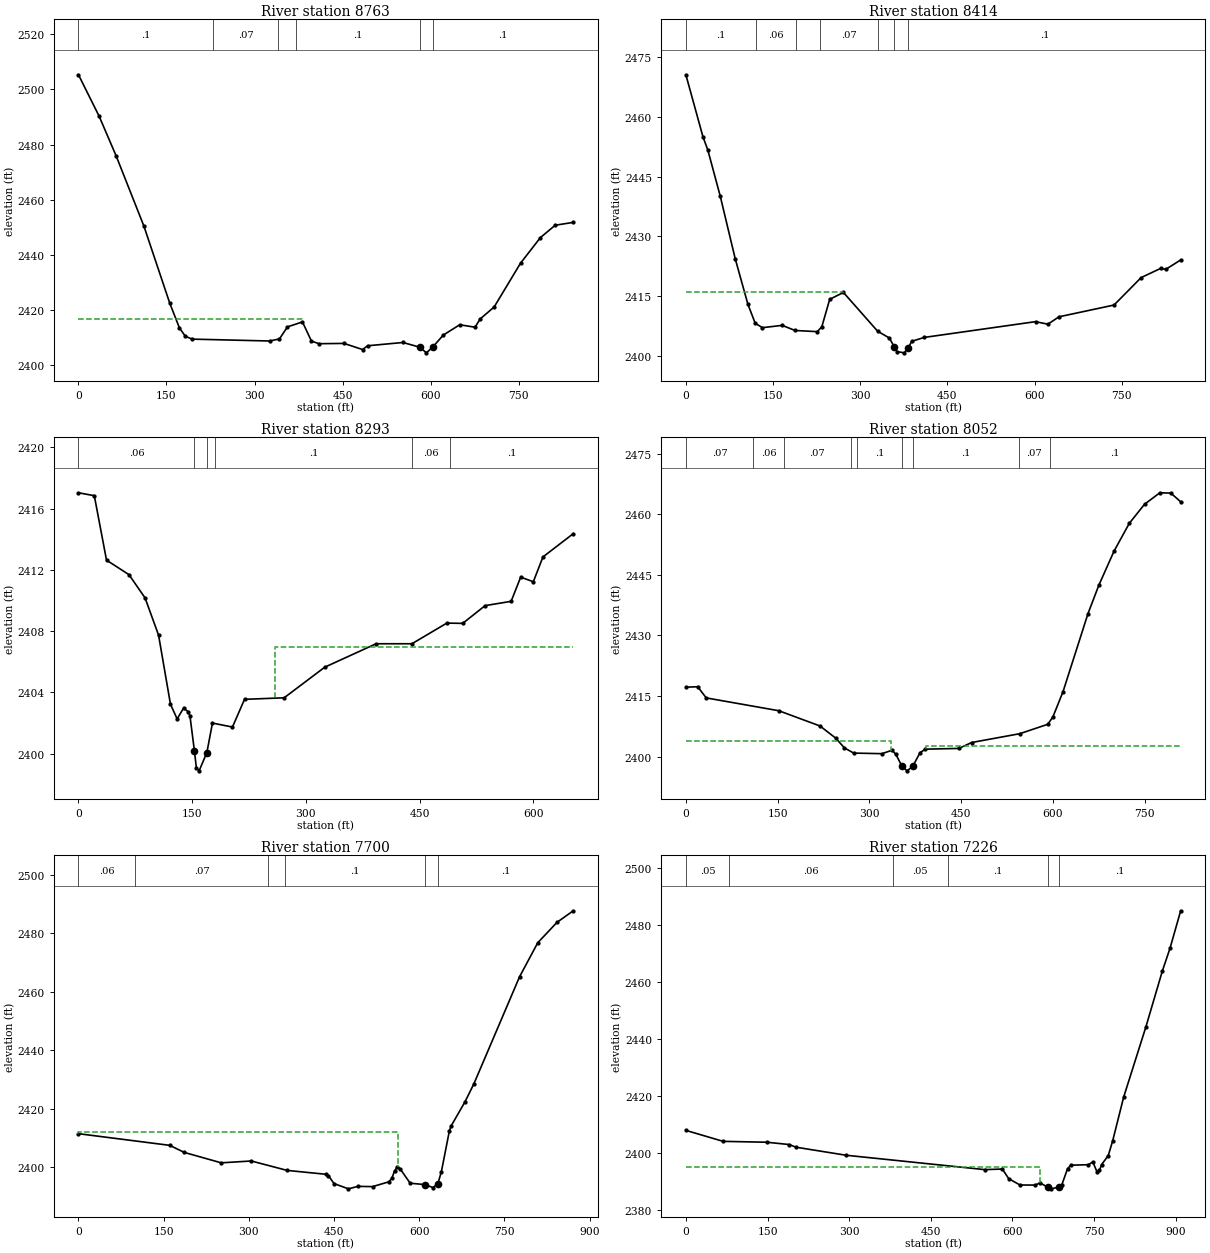
Type RM Length L Ch R = 1 ,8763    ,269.7,276.2,272.8
XS GIS Cut Line= 4
2257604.58787881394010.3072423822257420.38009288394346.925781857
2257122.19454776394475.4701627082257099.85344278394608.385587474
#Sta/Elev= 30
       0 2505.33    35.2 2490.28    64.3 2475.82   111.5 2450.37   155.7 2422.28
     172 2413.42   182.2 2410.32     194 2409.31   325.8 2408.63   342.5 2409.38
   356.1 2413.75   381.7 2415.56     397 2408.61   409.9 2407.65   452.6 2407.75
   484.1 2405.53   492.8  2406.9     553 2408.09   581.4 2406.39     593 2404.33
  603.82 2406.46   621.8  2410.8   649.7 2414.53   675.8 2413.64   684.5 2416.63
   708.4 2420.99   753.3 2436.89   787.2 2446.19   812.4 2450.68   843.2 2451.72
#Mann= 6 ,-1,0
       0      .1       0     230     .07       0     340     .06       0
     370      .1       0   581.4    .045       0  603.82      .1       0
#XS Ineff= 2 , 0
          380.34 2416.73
Permanent Ineff=
       F       F
Bank Sta=581.4,603.82
XS Rating Curve= 0 ,0
Exp/Cntr=0.3,0.1

Type RM Length L Ch R = 1 ,8414    ,210.6,193.3,169.9
XS GIS Cut Line= 3
2257539.45922967394042.6085673772257066.58366533394222.684712954
 2256954.7739344394549.464842852
#Sta/Elev= 30
       0  2470.5    29.3 2455.01    37.8 2451.64    59.2 2440.06    84.8 2424.48
   106.8 2412.99   119.2  2408.3   131.6 2407.16   165.7 2407.74   187.9 2406.46
   226.1 2406.17   233.9 2407.38   247.5 2414.27   271.1 2415.98     330 2406.27
   350.2 2404.57   358.8 2402.28   363.1 2401.18   375.9 2400.86   382.7 2402.18
   388.7 2403.75   410.1 2404.72   601.6 2408.67   622.8 2408.04   642.2 2409.89
   736.7 2412.83   783.4 2419.71   817.3 2422.03   825.7 2421.77   851.4 2424.12
#Mann= 7 ,-1,0
       0      .1       0     120     .06       0     190      .1       0
     230     .07       0     330      .1       0   358.8    .045       0
   382.7      .1       0
#XS Ineff= 2 , 0
          269.98 2416.11
Permanent Ineff=
       F       F
Bank Sta=358.8,382.7
XS Rating Curve= 0 ,0
Exp/Cntr=0.3,0.1

Type RM Length L Ch R = 1 ,8293    ,238.9,241.5,241.3
XS GIS Cut Line= 2
 2257179.7158721393846.1783730752256965.70942367 394463.02048913
#Sta/Elev= 30
       0 2417.03    20.9 2416.84      37 2412.63    66.7 2411.68    87.9 2410.16
   105.7 2407.73   121.4 2403.22   130.2 2402.26   138.7 2402.97     145 2402.72
   147.1 2402.47  153.04 2400.15   155.6 2399.06   159.2 2398.87   169.4 2400.06
   176.8 2401.99   203.2 2401.73   219.1 2403.54   271.4 2403.64     325 2405.64
   392.7 2407.17     440 2407.17   486.1 2408.52     507  2408.5   536.6 2409.66
   570.9 2409.94   583.5 2411.52   600.2 2411.22   612.9 2412.84   652.9 2414.36
#Mann= 6 ,-1,0
       0     .06       0  153.04    .045       0   169.4     .06       0
     180      .1       0     440     .06       0     490      .1       0
#XS Ineff= 2 , 0
                          259.51         2406.95
Permanent Ineff=
       F       F
Bank Sta=153.04,169.4
XS Rating Curve= 0 ,0
Exp/Cntr(USF)=0,0
Exp/Cntr=0.3,0.1

Type RM Length L Ch R = 1 ,8052    ,345.3,352.4,353.5
XS GIS Cut Line= 4
2257159.58638925  393749.97554972256935.78879613393917.823744545
2256849.86650591394125.6357953052256764.83598116394417.761107521
#Sta/Elev= 30
       0 2417.18    19.3  2417.3    33.3 2414.53     152 2411.35   219.3 2407.57
   244.7 2404.59   259.3 2402.14   274.3 2400.86   320.6 2400.71   337.1 2401.57
   343.3 2400.54   353.1 2397.65   361.6 2396.46   370.8 2397.55   382.9 2400.98
   391.6 2401.83   446.2 2402.01   467.2 2403.48   545.8 2405.66   591.6 2407.99
     600 2409.81   616.6 2416.09   657.3 2435.38     675 2442.41   699.9 2450.87
   724.9 2457.78   749.9 2462.52   774.9 2465.35   792.8 2465.27   808.9 2463.12
#Mann= 9 ,-1,0
       0     .07       0     110     .06       0     160     .07       0
     270     .06       0  279.75      .1       0   353.1    .045       0
   370.8      .1       0  544.62     .07       0  594.62      .1       0
#XS Ineff= 2 , 0
           335.6 2403.83  393.19         2402.51
Permanent Ineff=
       F       F
Bank Sta=353.1,370.8
XS Rating Curve= 0 ,0
Exp/Cntr(USF)=0,0
Exp/Cntr=0.3,0.1

Type RM Length L Ch R = 1 ,7700    ,453.8,473.4,488.4
XS GIS Cut Line= 3
2257048.00828059393690.814661616 2256752.9325486393764.971492431
2256432.39863283394232.790386603
#Sta/Elev= 30
       0 2411.54   160.7 2407.56   186.4 2405.14   251.4 2401.59   304.3 2402.22
   367.5    2399   435.4 2397.69   440.1 2397.24     450  2394.5   475.4 2392.71
     492 2393.55   517.9 2393.47   546.6 2395.11   551.8 2396.28   556.6 2398.82
   561.5 2400.22   566.3 2399.57   584.1 2394.63   609.9 2394.16   624.3 2393.15
     633 2394.52   639.1 2398.61   653.1 2412.45     656  2414.1   680.7 2422.45
   696.3 2428.56   776.8 2465.15   808.8 2476.74   842.7 2483.71   871.3 2487.65
#Mann= 6 ,-1,0
       0     .06       0     100     .07       0  334.25     .06       0
  364.25      .1       0   609.9    .045       0     633      .1       0
#XS Ineff= 2 , 0
           562.3    2412
Permanent Ineff=
       F       F
Bank Sta=609.9,633
XS Rating Curve= 0 ,0
Exp/Cntr=0.3,0.1

Type RM Length L Ch R = 1 ,7226    ,171.2,172.9,174.3
XS GIS Cut Line= 3
2257005.58383154393464.7541317512256621.87779051393583.005086392
2256120.86607128393664.388151187
#Sta/Elev= 30
       0 2407.85    68.4 2403.99   148.6 2403.68   189.8 2402.87   202.4 2401.93
   294.5  2399.1   549.1 2394.05   581.5 2394.25   593.1 2390.88   613.8 2388.64
     642 2388.61   650.4 2389.38   664.5 2387.93   670.7 2387.29   686.4 2387.93
   690.8 2388.75   701.2 2394.35   707.2  2395.6   739.6 2395.78   747.7 2396.74
   755.8 2393.07   759.9 2393.76   763.9 2395.84   776.1 2399.01   784.2 2404.21
   804.4 2419.59     845 2444.12   875.5 2463.94   889.5 2471.89   909.1 2485.08
#Mann= 6 ,-1,0
       0     .05       0      80     .06       0     380     .05       0
  481.51      .1       0   664.5    .045       0   686.4      .1       0
#XS Ineff= 2 , 0
           649.9 2394.94
Permanent Ineff=
       F       F
Bank Sta=664.5,686.4
XS Rating Curve= 0 ,0
Exp/Cntr=0.3,0.1

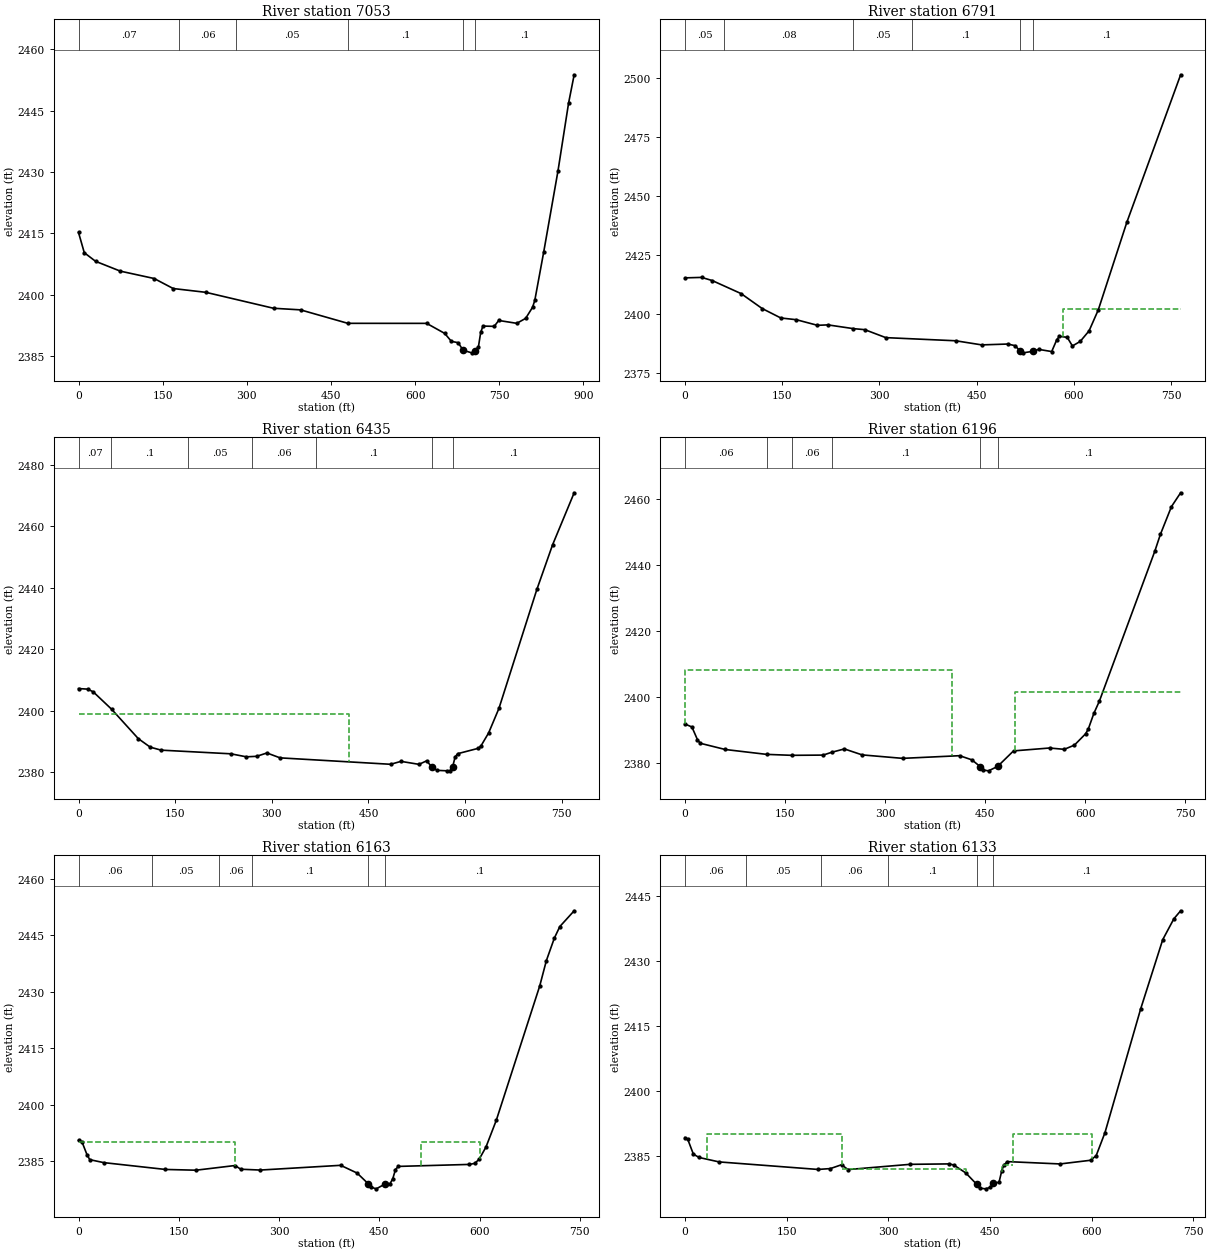
Type RM Length L Ch R = 1 ,7053    ,259.8,262.1,263.6
XS GIS Cut Line= 2
 2257018.4343669 393396.757741062256138.26713937393472.896774583
#Sta/Elev= 30
       0 2415.22    10.3 2410.27    30.4 2408.17    74.5 2405.77   134.8 2403.97
   168.8 2401.52   227.1 2400.59   347.6  2396.7   395.7 2396.31     480 2393.02
   620.6 2393.01   652.7 2390.56   664.7 2388.61   676.8 2388.29   685.52386.438
   700.9 2385.81   706.6 2386.33   712.9 2387.33   716.9  2390.8   720.9 2392.35
     741 2392.28     749 2393.72   781.2 2393.02     797 2394.23   809.3 2396.93
   813.3 2398.61   829.3 2410.51   854.7 2430.29   873.5 2446.79   883.5 2453.74
#Mann= 6 ,-1,0
       0     .07       0     180     .06       0     280     .05       0
     480      .1       0   685.5    .045       0   706.6      .1       0
Bank Sta=685.5,706.6
XS Rating Curve= 0 ,0
Exp/Cntr(USF)=0,0
Exp/Cntr=0.3,0.1

Type RM Length L Ch R = 1 ,6791    ,355.8,356.1,355.3
XS GIS Cut Line= 3
2256889.53800216393151.4653714932256583.43733262393204.624611234
2256129.20548309393203.042500639
#Sta/Elev= 30
       0 2415.32    25.7 2415.52      42 2414.19    86.6 2408.67   119.1 2402.36
   147.9 2398.36   171.9 2397.63   204.4 2395.26   220.6 2395.44     260 2393.85
   277.5 2393.42   309.9 2390.05   417.9 2388.72   457.9 2386.98   497.9 2387.34
   509.9 2386.63   516.7 2384.41   521.9 2383.62   536.6 2384.25   545.9 2385.08
   565.9 2384.16   573.9 2389.23   577.9 2390.61   589.9 2390.17   597.9 2386.53
   609.9 2388.44   623.6 2392.91   637.9 2401.84   681.9 2438.85   764.9  2501.2
#Mann= 6 ,-1,0
       0     .05       0      60     .08       0     260     .05       0
  350.68      .1       0   516.7    .045       0   536.6      .1       0
#XS Ineff= 2 , 0
                          583.12         2402.29
Permanent Ineff=
       F       F
Bank Sta=516.7,536.6
XS Rating Curve= 0 ,0
Exp/Cntr=0.3,0.1

Type RM Length L Ch R = 1 ,6435    ,246.3,238.7,231
XS GIS Cut Line= 4
2256880.57726686392947.8879168032256699.54151071392843.437203811
2256256.62779139392852.7690340812256144.02892406392885.185069125
#Sta/Elev= 30
       0 2407.29    14.3  2407.1    22.8 2406.23    51.3 2400.58    92.8    2391
   111.3 2388.23   128.2 2387.26   236.4 2386.07   260.4 2385.09   276.4 2385.25
   292.4 2386.34   312.8 2384.75   484.4 2382.66   500.4 2383.61   528.4 2382.64
   540.4  2383.8   548.4 2381.72   556.5 2380.69   572.5 2380.53   576.5 2380.59
   580.5 2381.76   584.5 2385.06   588.5 2386.11   620.5 2387.86   624.5 2388.61
   636.5 2392.88   652.5 2400.86   711.3 2439.52   735.7 2454.04   769.2 2470.96
#Mann= 7 ,-1,0
       0     .07       0      50      .1       0     170     .05       0
  269.01     .06       0  369.01      .1       0   548.4    .045       0
   580.5      .1       0
#XS Ineff= 2 , 0
          419.28  2399.1
Permanent Ineff=
       F       F
Bank Sta=548.4,580.5
XS Rating Curve= 0 ,0
Exp/Cntr=0.3,0.1

Type RM Length L Ch R = 1 ,6196    ,32.1,33.5,35.2
XS GIS Cut Line= 2
2256754.22825596392491.955508647 2256038.9741554392692.191681054
#Sta/Elev= 30
       0 2391.84    10.4 2390.93    18.7 2387.08    22.9 2385.99    60.3  2384.1
   122.3 2382.62     160 2382.33   207.1  2382.4   220.1 2383.27   238.9 2384.27
   265.5 2382.46   326.1 2381.41   411.6 2382.22     430 2380.95   442.4  2378.9
   447.3 2377.85   454.9 2377.62   468.5 2378.96   492.3 2383.67   546.3 2384.55
   568.4 2384.15   583.6 2385.43   600.3 2388.86   604.4 2390.32   612.7 2395.05
     621 2398.79   704.1 2444.32   712.4  2449.4     729 2457.84742.7536 2462.04
#Mann= 6 ,-1,0
       0     .06       0   122.3     .05       0     160     .06       0
   220.1      .1       0   442.4    .045       0   468.5      .1       0
#XS Ineff= 2 , 0
             400  2408.3  494.79         2401.51
Permanent Ineff=
       F       F
Bank Sta=442.4,468.5
XS Rating Curve= 0 ,0
Exp/Cntr(USF)=0,0
Exp/Cntr=0.5,0.3

Type RM Length L Ch R = 1 ,6163    ,29.7,29.9,30.1
XS GIS Cut Line= 3
2256740.23795571392458.7285455412256417.58665607392557.535041095
2256023.23506761392645.848811457
#Sta/Elev= 30
       0 2390.45     5.2 2390.06    12.6 2386.69    16.8 2385.33    37.7 2384.54
   130.1 2382.72   175.8 2382.52   234.3 2383.77   242.7 2382.78     272 2382.56
   392.2 2383.82   416.8 2381.76   433.2 2378.96   437.3 2378.03   445.4 2377.56
   458.9 2378.87     466 2378.93   470.1 2380.21   474.2 2382.67   478.3 2383.53
   584.8 2384.06   592.9 2384.34   599.6 2385.49   609.6 2388.68     625 2395.78
     690 2431.54     700 2438.32   711.9 2444.29   720.1 2447.37741.5607 2451.57
#Mann= 6 ,-1,0
       0     .06       0     110     .05       0     210     .06       0
     260      .1       0   433.2    .045       0   458.9      .1       0
#XS Ineff= 4 ,-1
       0     234    2390     234     410  2382.3     480     513  2383.5
     513     600    2390
Permanent Ineff=
       F       F       F       F
Bank Sta=433.2,458.9
XS Rating Curve= 0 ,0
Exp/Cntr(USF)=0,0
Exp/Cntr=0.5,0.3

Type RM Length L Ch R = 1 ,6133    ,64.5,61.8,59.7
XS GIS Cut Line= 3
2256727.99644298392425.5015824342256413.21468724392528.680046818
2256022.36067385392613.496242117
#Sta/Elev= 30
       0 2389.23       4 2388.87    12.4 2385.41    20.9 2384.64    50.3 2383.62
   196.2 2381.88   214.5 2382.08     231 2382.97   240.5 2381.85     332 2383.06
   389.6 2383.16   396.5 2382.91   414.2 2381.08   430.1 2378.49   434.7 2377.56
   443.5  2377.4   450.3 2377.73   455.1 2378.67   463.3 2378.92   467.4 2381.62
   470.4 2382.87   475.6 2383.69   553.4 2383.15   598.4    2384   606.6 2385.06
   619.5 2390.34   672.2 2418.94   704.8 2434.96   721.2 2439.77731.2111 2441.63
#Mann= 6 ,-1,0
       0     .06       0      90     .05       0     200     .06       0
     300      .1       0   430.1    .045       0   455.1      .1       0
#XS Ineff= 4 ,-1
      33     232    2390     232     414    2382     467     484    2383
     484     600    2390
Permanent Ineff=
       F       F       F       F
Bank Sta=430.1,455.1
XS Rating Curve= 0 ,0
Exp/Cntr(USF)=0,0
Exp/Cntr=0.5,0.3

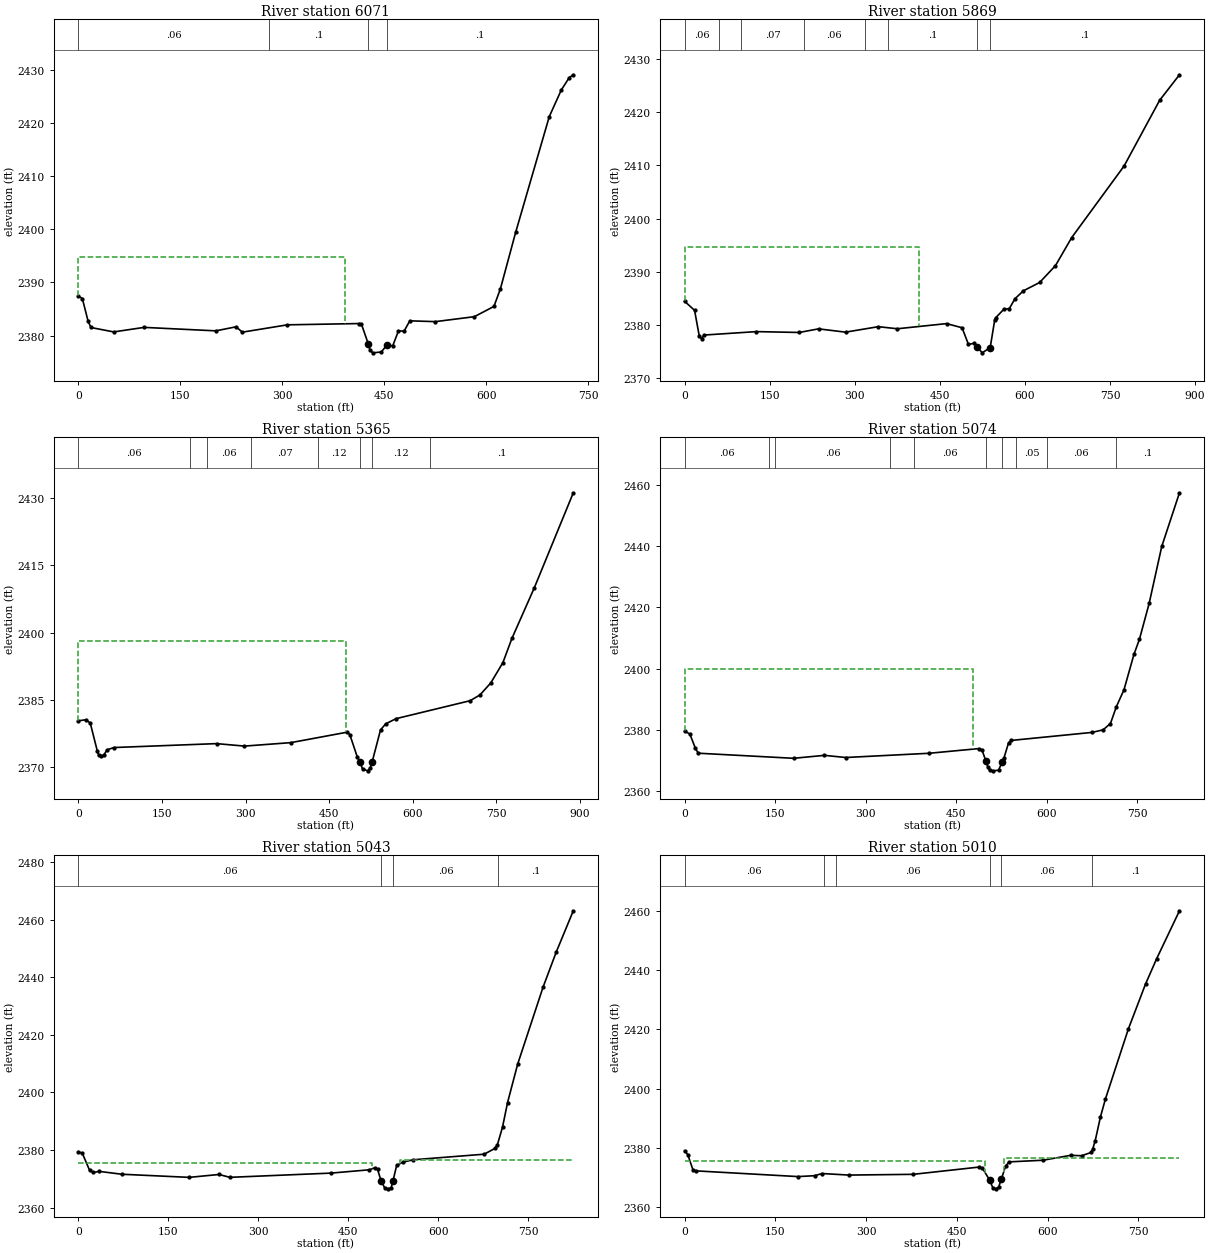
Type RM Length L Ch R = 1 ,6071    ,210.3,202.3,194.7
XS GIS Cut Line= 2
 2256709.6341739392361.6708375182256014.49112995392577.646097712
#Sta/Elev= 30
       0 2387.45     5.7 2386.99    14.1 2382.76    18.3 2381.55    51.8 2380.72
    96.6 2381.57   202.1 2380.92   231.9 2381.68     241 2380.67   307.3 2382.05
     413 2382.29   416.3 2382.17  426.38 2378.45   428.8 2377.28     433 2376.79
   445.5 2376.95   453.9 2378.29   462.3  2378.1   470.7 2380.91     479 2380.86
   487.4  2382.8   525.1 2382.65   582.4 2383.58   611.2 2385.51   620.7 2388.81
   643.1 2399.41   692.6 2421.16   710.2 2426.14     722 2428.49727.9211 2429.01
#Mann= 4 ,-1,0
       0     .06       0     280      .1       0  426.38    .045       0
   453.9      .1       0
#XS Ineff= 2 , 0
          392.45 2394.81
Permanent Ineff=
       F       F
Bank Sta=426.38,453.9
XS Rating Curve= 0 ,0
Exp/Cntr(USF)=0,0
Exp/Cntr=0.3,0.1

Type RM Length L Ch R = 1 ,5869    ,500.5,503.7,504
XS GIS Cut Line= 4
2256641.15227428392124.9416059542256381.43368817       392190.05
2256061.80162621392403.8804163962255962.34029164392600.323690649
#Sta/Elev= 30
       0 2384.39    17.5 2382.69    25.8 2377.85    29.9 2377.34      34 2378.03
   126.3 2378.68   202.1 2378.52   236.1  2379.2   283.7 2378.58   341.5 2379.61
   375.1 2379.22   461.8 2380.19   489.2 2379.41   500.3 2376.29   510.8 2376.47
     516 2375.78   524.7 2374.68   538.8 2375.68   546.7 2380.88   548.4 2381.28
   562.8  2382.9   572.5 2383.02   582.3 2384.86   597.1 2386.36   625.9 2387.94
   653.8 2391.11   682.5 2396.41   774.8 2409.89   837.6 2422.29   872.5 2427.09
#Mann= 8 ,-1,0
       0     .06       0      60     .05       0     100     .07       0
     210     .06       0  317.76     .07       0  357.76      .1       0
     516    .045       0   538.8      .1       0
#XS Ineff= 2 , 0
          413.21 2394.67
Permanent Ineff=
       F       F
Bank Sta=516,538.8
XS Rating Curve= 0 ,0
Exp/Cntr=0.3,0.1

Type RM Length L Ch R = 1 ,5365    ,291.2,291.5,291.8
XS GIS Cut Line= 3
2256419.78738558391634.7815895042255762.44004991392007.155505666
2255746.31179126  392138.5784697
#Sta/Elev= 30
       0 2380.37    13.2 2380.59    21.1 2379.88    33.8 2373.64    36.3 2372.65
    39.6 2372.42    45.5 2372.75    51.4 2373.91    63.9 2374.41   247.8 2375.28
   297.9 2374.73   381.1  2375.5   482.3 2377.83   486.9 2377.29   500.4 2372.26
   505.2 2371.24   509.8 2369.58     519 2369.22   523.6 2369.84   526.8 2371.13
     542 2378.34   551.2 2379.67   569.6 2380.83   702.9 2384.84   720.5 2386.13
   739.7 2388.77   761.6 2393.32   777.7 2398.69     818 2409.99   887.9 2431.13
#Mann= 8 ,-1,0
       0     .06       0     200     .07       0     230     .06       0
     310     .07       0     430     .12       0   505.2    .045       0
   526.8     .12       0     630      .1       0
#XS Ineff= 2 , 0
          480.19 2398.13
Permanent Ineff=
       F       F
Bank Sta=505.2,526.8
XS Rating Curve= 0 ,0
Exp/Cntr=0.3,0.1

Type RM Length L Ch R = 1 ,5074    ,31.1,31.1,31.3
XS GIS Cut Line= 3
 2256279.7445327391385.9918535772255662.81115338391726.033873674
2255552.05460969391760.038075684
#Sta/Elev= 30
       0  2379.6     8.6 2378.68    17.8 2374.01    22.6  2372.4   180.6 2370.74
   231.7  2371.7     267    2371   405.4 2372.38   487.2  2373.9   492.8 2373.51
   499.6 2369.74   499.6 2369.73   502.6 2367.79   505.5 2366.85   511.1 2366.65
   520.3 2366.85   526.1 2369.38   529.1 2370.68   536.9 2375.75   540.9 2376.56
   675.5 2379.19   693.7 2380.02   705.9 2382.09   715.7 2387.58   728.3 2393.09
   744.9 2404.68   753.9 2409.54     770 2421.24   790.9 2439.83820.2987 2457.35
#Mann= 10 ,-1,0
       0     .06       0     140     .05       0     150     .06       0
     340     .05       0     380     .06       0   499.6    .045       0
   526.1     .06       0     550     .05       0     600     .06       0
  714.44      .1       0
#XS Ineff= 2 , 0
          477.36 2399.72
Permanent Ineff=
       F       F
Bank Sta=499.6,526.1
XS Rating Curve= 0 ,0
Exp/Cntr(USF)=0,0
Exp/Cntr=0.5,0.3

Type RM Length L Ch R = 1 ,5043    ,33.2,33,32.9
XS GIS Cut Line= 3
2256265.75566659391360.2521544862255660.29289933391691.251461213
2255532.50454429391735.084514917
#Sta/Elev= 30
       0 2379.42     6.4 2378.88    18.6 2372.92    24.6 2372.19    34.3 2372.58
    72.6 2371.58   184.6  2370.5   234.3  2371.5   252.5 2370.51   421.2 2371.98
     485 2373.13   494.1 2373.84   498.7 2373.32   504.5  2369.3   510.6 2366.87
   516.9 2366.51   521.5 2366.91   524.6 2369.39   530.6 2374.66   541.2  2375.8
     558 2376.61   676.5 2378.55   694.4 2380.56   698.6 2381.87   707.1 2387.95
   715.5 2396.51   732.4 2409.89   774.7 2436.62   796.5 2448.73825.1301 2463.17
#Mann= 4 ,-1,0
       0     .06       0   504.5    .045       0   524.6     .06       0
  700.03      .1       0
#XS Ineff= 2 , 0
          488.86  2375.4  536.43          2376.4
Permanent Ineff=
       F       F
Bank Sta=504.5,524.6
XS Rating Curve= 0 ,0
Exp/Cntr(USF)=0,0
Exp/Cntr=0.5,0.3

Type RM Length L Ch R = 1 ,5010    ,65.8,66,66.5
XS GIS Cut Line= 4
2256252.87968138391343.3206695622256021.87589217391454.380183605
2255656.75160458391656.5467726422255520.46536927391703.409370407
#Sta/Elev= 30
       0 2378.99     5.2 2377.71    13.9 2372.46    18.5 2372.22   187.2 2370.29
   214.7 2370.58   227.1 2371.32   271.4  2370.8   377.7 2371.05   486.9 2373.51
   492.1 2373.14   503.9 2369.15   509.7 2366.32   514.3 2366.15   518.9 2366.74
   523.4  2369.4   530.4 2373.81   536.2 2375.26   592.2 2375.81   637.8 2377.47
     656 2377.33   671.6 2378.43   674.3 2379.54   678.5  2382.4   687.2 2390.46
   695.4 2396.49   733.5 2420.26   761.7 2435.33     780 2443.85817.7896 2460.07
#Mann= 6 ,-1,0
       0     .06       0     230     .05       0     250     .06       0
   503.9    .045       0   523.4     .06       0  673.67      .1       0
#XS Ineff= 2 , 0
          496.57  2375.4  527.39          2376.4
Permanent Ineff=
       F       F
Bank Sta=503.9,523.4
XS Rating Curve= 0 ,0
Exp/Cntr(USF)=0,0
Exp/Cntr=0.5,0.3