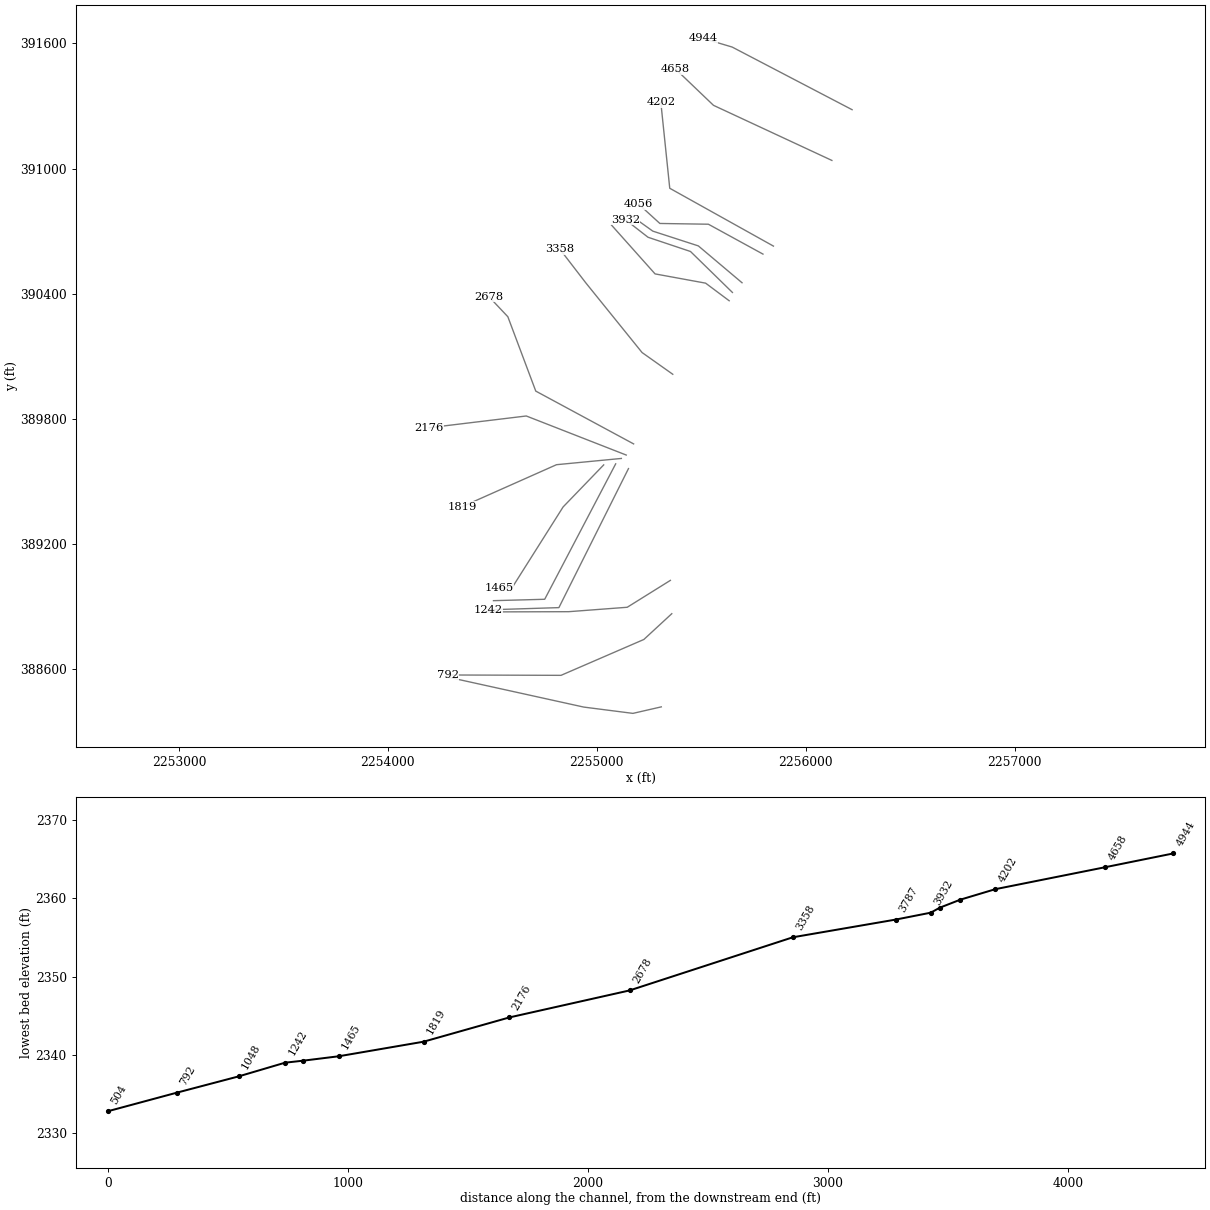
HEC-RAS study ANTHNYCK.prj: ANTHNYCK

--- ANTHNYCK.g01 (geometry) --- (continued)

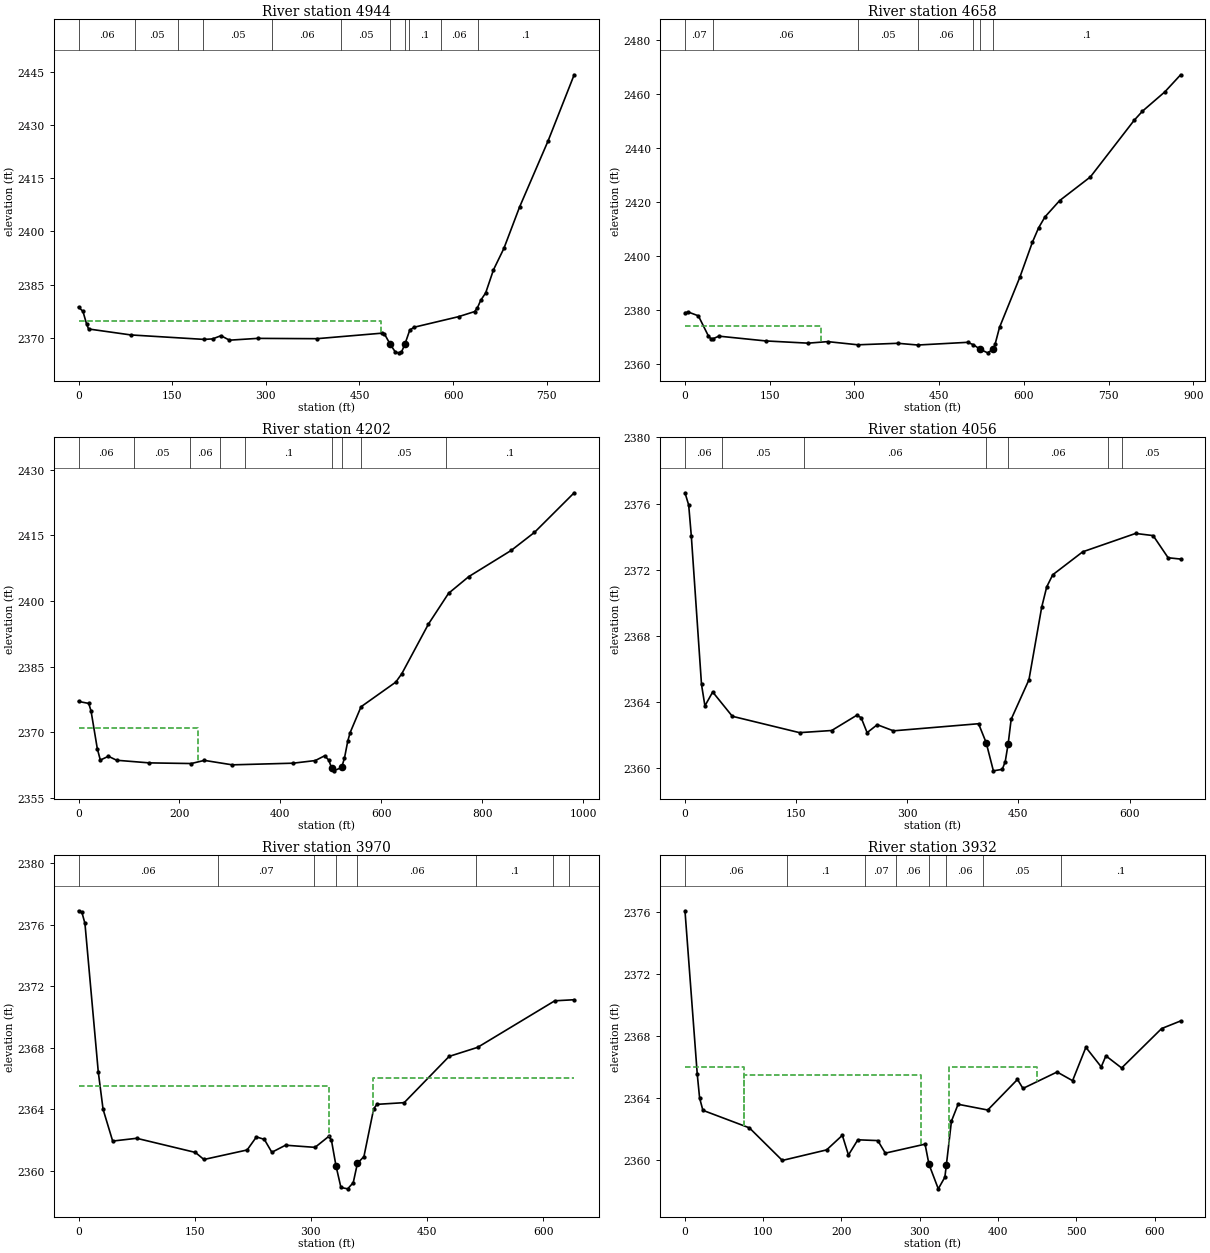
Type RM Length L Ch R = 1 ,4944    ,284,285.6,286.6
XS GIS Cut Line= 3
 2256222.4231636 391282.036150292255648.23792395391582.244676604
2255508.33492139391624.021267645
#Sta/Elev= 30
       0 2378.66     7.1 2377.43    12.9  2373.9    16.1 2372.47    83.8 2370.79
   201.1 2369.53   214.7 2369.67   228.2 2370.57   241.8 2369.31   286.9 2369.82
   381.7 2369.73   485.5 2371.28   490.1 2371.05   499.2 2368.18   507.5 2365.96
   512.6 2365.74   517.1 2365.88   522.7 2368.12   530.6 2372.16   537.5 2372.96
   608.7 2375.94   634.5 2377.38     639 2378.46   644.2 2380.54   652.2 2382.65
   664.7 2389.16   681.4 2395.21   706.4 2406.83   752.4 2425.62793.9377 2444.17
#Mann= 11 ,-1,0
       0     .06       0      90     .05       0     160     .06       0
     200     .05       0     310     .06       0     420     .05       0
   499.2    .045       0   522.7     .05       0     530      .1       0
     580     .06       0     640      .1       0
#XS Ineff= 2 , 0
          483.76 2374.82
Permanent Ineff=
       F       F
Bank Sta=499.2,522.7
XS Rating Curve= 0 ,0
Exp/Cntr(USF)=0,0
Exp/Cntr=0.3,0.1

Type RM Length L Ch R = 1 ,4658    ,459,456.9,455
XS GIS Cut Line= 3
2256125.65047342391038.9096319392255558.86845251391302.942330868
2255376.76431515391477.214579022
#Sta/Elev= 30
       0 2378.86       6 2379.09    23.7  2377.7    41.3 2370.29    45.8  2369.2
    50.2 2369.25      60 2370.16   142.8 2368.39   217.9 2367.56   252.7 2368.13
   306.1 2366.95   376.7 2367.51   412.2 2366.87   500.3 2367.87   510.6 2366.96
   522.3 2365.31   535.6 2363.97   545.3  2365.3   548.8 2367.08   556.7  2373.4
   592.9 2392.12     615 2405.04   625.9 2410.34   637.2  2414.4   663.2 2420.45
   717.6 2429.23   795.1 2450.24   809.8 2453.62   849.4 2460.78   877.3 2467.11
#Mann= 7 ,-1,0
       0     .07       0    50.2     .06       0   306.1     .05       0
   412.2     .06       0   510.6      .1       0   522.3    .045       0
   545.3      .1       0
#XS Ineff= 2 , 0
             240 2374.07
Permanent Ineff=
       F       F
Bank Sta=522.3,545.3
XS Rating Curve= 0 ,0
Exp/Cntr=0.3,0.1

Type RM Length L Ch R = 1 ,4202    ,129.9,145.7,156.9
XS GIS Cut Line= 3
2255845.89325065390628.3424821722255349.46675208390905.488564195
2255306.82889331391316.639345218
#Sta/Elev= 30
       0 2377.04    20.3 2376.58    24.9 2374.81    37.2 2366.26    43.2 2363.63
    59.2  2364.5    75.6 2363.59   140.1 2362.99   223.3 2362.84   249.3 2363.56
   304.7 2362.54   425.2 2362.92     469 2363.52   487.6 2364.61   495.8 2363.61
   501.3 2361.85   505.9 2361.17   521.22361.941   526.9  2364.1   533.4 2367.97
     538 2369.88   559.7 2375.82   628.6 2381.46   640.6 2383.41   693.3 2394.74
   733.1 2401.76   773.1 2405.57   857.3 2411.57   903.3 2415.69   981.9 2424.74
#Mann= 9 ,-1,0
       0     .06       0     110     .05       0     220     .06       0
     280     .05       0     330      .1       0   501.3    .045       0
   521.2      .1       0     560     .05       0  728.55      .1       0
#XS Ineff= 2 , 0
          236.95  2370.9
Permanent Ineff=
       F       F
Bank Sta=501.3,521.2
XS Rating Curve= 0 ,0
Exp/Cntr(USF)=0,0
Exp/Cntr=0.3,0.1

Type RM Length L Ch R = 1 ,4056    ,92.4,85.3,79
XS GIS Cut Line= 4
2255795.73064629390589.9987833212255534.42076115390733.210994542
2255302.09917671390736.8181597642255199.66784266390830.196085447
#Sta/Elev= 30
       0 2376.65       5 2375.91     8.6 2374.01    22.3 2365.06    26.9 2363.76
    37.4  2364.6    63.9 2363.13   154.6 2362.14     198 2362.27   231.8 2363.19
   237.7 2363.05   245.8 2362.14   259.5 2362.62   281.3 2362.25   396.2 2362.68
   406.5 2361.53   416.2 2359.83   428.2 2359.92   432.2 2360.39   436.2 2361.48
   440.2 2362.95   464.2 2365.34   481.4 2369.73   488.2 2370.96   496.3 2371.69
   536.8 2373.08   608.1 2374.19   631.8 2374.06     652 2372.72   668.9 2372.64
#Mann= 7 ,-1,0
       0     .06       0      50     .05       0     160     .06       0
   406.5    .045       0   436.2     .06       0  570.33      .1       0
  590.33     .05       0
Bank Sta=406.5,436.2
XS Rating Curve= 0 ,0
Exp/Cntr=0.5,0.3

Type RM Length L Ch R = 1 ,3970    ,37.2,37.8,36.6
XS GIS Cut Line= 4
 2255695.4685674390452.7100815542255486.39052524390629.279037897
2255268.38842029390700.034107045 2255156.8376356390779.713238968
#Sta/Elev= 30
       0 2376.91     4.3 2376.82     8.3 2376.09    25.5 2366.43    31.7 2363.99
    44.1 2361.92    75.1  2362.1   150.9 2361.18   161.9 2360.72   217.7 2361.34
   229.7 2362.19   239.9 2362.03   249.6 2361.19   267.3 2361.65   305.4 2361.51
     323 2362.22   326.5 2361.99   332.5 2360.29   338.8  2358.9   347.5 2358.81
   354.7 2359.21   360.1 2360.47   368.5 2360.91   381.1 2364.02   385.3 2364.31
   420.5 2364.42   478.5 2367.43   515.3 2368.02   614.9 2371.05639.9428 2371.12
#Mann= 8 ,-1,0
       0     .06       0     180     .07       0  303.66     .06       0
   332.5    .045       0   360.1     .06       0  512.86      .1       0
  612.86     .05       0  632.86      .1       0
#XS Ineff= 2 , 0
          322.92  2365.5  379.72            2366
Permanent Ineff=
       F       F
Bank Sta=332.5,360.1
XS Rating Curve= 0 ,0
Exp/Cntr(USF)=0,0
Exp/Cntr=0.5,0.3

Type RM Length L Ch R = 1 ,3932    ,143.8,145.7,150.9
XS GIS Cut Line= 4
2255649.57338741390406.1774685112255448.78197497 390602.50684957
 2255245.4408303390670.7121864972255136.43977783390755.490782863
#Sta/Elev= 30
       0 2376.09    15.7 2365.55    18.7 2364.02    22.9 2363.23    82.3  2362.1
   124.4    2360     181 2360.68   201.1 2361.62   208.9 2360.35   220.9 2361.33
   246.4 2361.28     256 2360.47   306.8 2361.05   311.8 2359.75   323.7 2358.17
   332.1 2358.92     334  2359.7   340.5 2362.53     349 2363.62   386.9 2363.25
   424.9 2365.22   431.9 2364.64   475.5  2365.7   495.3 2365.14   512.3 2367.29
   531.9 2366.03   537.9 2366.74     558 2365.96   609.1  2368.5633.3889 2368.99
#Mann= 8 ,-1,0
       0     .06       0     130      .1       0     230     .07       0
     270     .06       0   311.8    .045       0     334     .06       0
  380.82     .05       0  480.82      .1       0
#XS Ineff= 3 ,-1
       0      75    2366      75     302  2365.5     337     450    2366
Permanent Ineff=
       F       F       F
Bank Sta=311.8,334
XS Rating Curve= 0 ,0
Exp/Cntr(USF)=0,0
Exp/Cntr=0.5,0.3

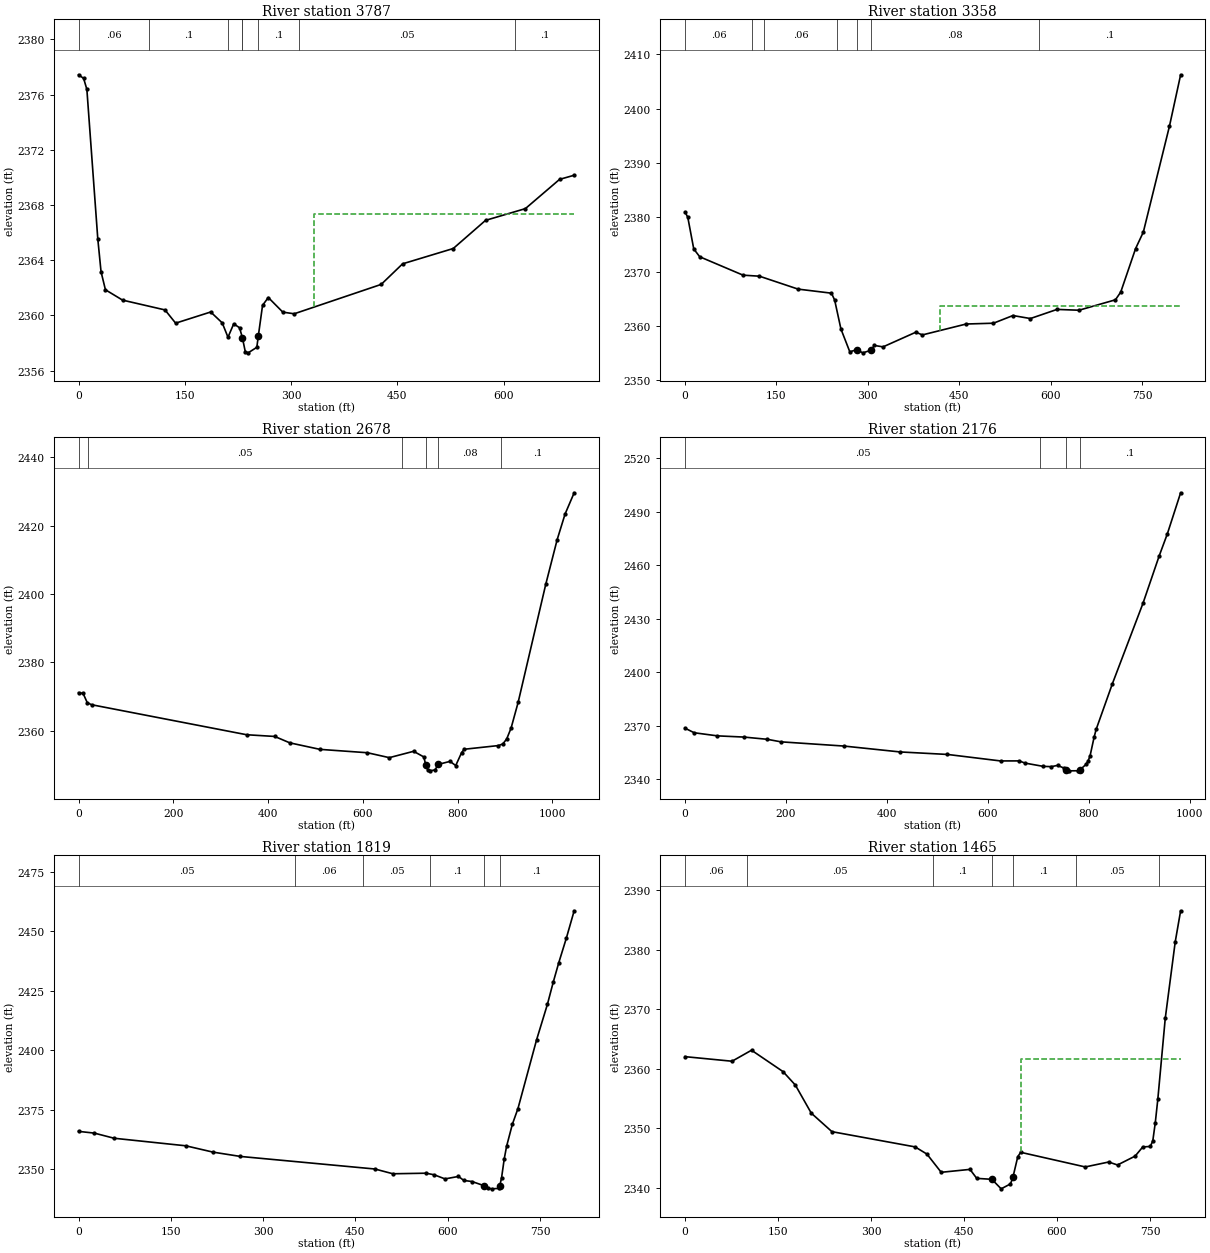
Type RM Length L Ch R = 1 ,3787    ,445.8,428.7,412.7
XS GIS Cut Line= 4
2255633.98087554390366.4158525722255521.18556264390450.745708426
2255279.18674756 390495.095694452255070.98227271390728.595143326
#Sta/Elev= 30
       0 2377.44     7.2 2377.18    11.8 2376.38    27.2 2365.56    31.8 2363.17
      38 2361.86    62.2 2361.11   122.1  2360.4   137.1 2359.44   186.6 2360.25
   202.9 2359.46     211 2358.42   219.1 2359.39   227.3 2359.11   231.3  2358.4
   235.4 2357.38   239.5 2357.29   251.7 2357.69   253.8  2358.5   259.8 2360.73
   267.9  2361.3   288.4 2360.24   304.5 2360.12   427.3 2362.25   457.5 2363.74
     529 2364.85   574.6 2366.89   630.8 2367.74   679.1 2369.86   699.7 2370.16
#Mann= 8 ,-1,0
       0     .06       0     100      .1       0  210.83     .05       0
  230.83      .1       0   231.3    .045       0   253.8      .1       0
  310.83     .05       0  616.86      .1       0
#XS Ineff= 2 , 0
                          332.43         2367.37
Permanent Ineff=
       F       F
Bank Sta=231.3,253.8
XS Rating Curve= 0 ,0
Exp/Cntr=0.3,0.1

Type RM Length L Ch R = 1 ,3358    ,685.8,680.5,669.5
XS GIS Cut Line= 4
2255363.90821191390014.0842891612255216.92441637390118.251466336
2254947.86480167390451.7554580252254823.08257084 390613.95171827
#Sta/Elev= 30
       0 2380.99     4.6 2380.01    14.4 2374.17    24.2 2372.73    95.3 2369.34
   122.2 2369.15   185.6 2366.77   240.4 2366.02   245.6 2364.75   255.9 2359.42
   270.5 2355.21   281.6 2355.62   291.8 2355.03   305.1  2355.5   310.8 2356.39
     325 2356.13   378.8 2358.83   389.5 2358.33   461.4 2360.34   506.2 2360.49
   538.1  2361.9   566.8 2361.35   610.5 2363.03   646.5 2362.88   706.3  2364.8
     715 2366.22   739.4 2374.24   752.1 2377.28   794.9 2396.76   813.3 2406.26
#Mann= 7 ,-1,0
       0     .06       0     110      .1       0     130     .06       0
  250.15     .08       0   281.6    .045       0   305.1     .08       0
  580.15      .1       0
#XS Ineff= 2 , 0
                          418.52         2363.59
Permanent Ineff=
       F       F
Bank Sta=281.6,305.1
XS Rating Curve= 0 ,0
Exp/Cntr=0.3,0.1

Type RM Length L Ch R = 1 ,2678    ,465.9,501.1,527.9
XS GIS Cut Line= 4
2255176.46752268389680.3881780652254708.00820447389933.442982633
2254574.31076872390289.8531320482254483.04348573390386.689259369
#Sta/Elev= 30
       0 2371.14     9.7 2370.91    18.5 2368.19    27.6  2367.6   354.9 2358.81
   414.1 2358.31   445.9 2356.44   509.5 2354.53   609.8 2353.54     656  2352.1
   707.3 2353.96   728.7 2352.32   732.9 2350.08   737.2 2348.46   741.5 2348.24
   752.7 2348.51   758.9 2350.11   784.2 2351.01   796.2 2349.78   808.6 2353.57
   814.1 2354.56   886.3 2355.64   895.6 2356.11   903.8 2357.58   913.1 2360.78
   927.9 2368.27   986.2 2402.84  1010.3 2415.93    1027 2423.44  1046.2 2429.66
#Mann= 6 ,-1,0
       0     .06       0      20     .05       0  682.44     .08       0
   732.9    .045       0   758.9     .08       0  892.44      .1       0
Bank Sta=732.9,758.9
XS Rating Curve= 0 ,0
Exp/Cntr=0.3,0.1

Type RM Length L Ch R = 1 ,2176    ,350.7,357.6,364.3
XS GIS Cut Line= 3
2255141.11220447389626.9731211912254662.58518144389814.217464681
2254198.00971563389757.968709658
#Sta/Elev= 30
       0 2368.71    18.2 2366.14    64.2  2364.4   116.7 2363.72     163 2362.47
     190 2361.05   314.6 2358.69   426.2 2355.38     520 2353.98   625.1 2350.34
   662.1 2350.36   673.4 2349.14   709.7 2347.29   725.8 2347.15   737.9 2347.84
     750 2346.42   755.4 2345.17   761.4 2344.79   778.2 2344.84   782.2 2345.31
   794.3 2348.39   798.3 2350.16   802.4 2353.18   810.4 2363.64   814.4 2367.98
   846.7 2393.69   907.1 2438.61   939.4 2465.34   955.5 2477.65   981.8 2500.66
#Mann= 4 ,-1,0
       0     .05       0  703.86      .1       0   755.4    .045       0
   782.2      .1       0
Bank Sta=755.4,782.2
XS Rating Curve= 0 ,0
Exp/Cntr=0.3,0.1

Type RM Length L Ch R = 1 ,1819    ,338.9,353.5,367.6
XS GIS Cut Line= 3
2255117.78371335389610.6949893352254807.22728883389580.744869786
2254356.43796499389380.002301166
#Sta/Elev= 30
       0 2365.83    25.7  2365.1    57.9 2362.94   174.4 2359.77   218.6 2357.11
   263.1  2355.3   481.7 2350.02   510.9 2348.02   564.9 2348.26   578.1 2347.58
   595.6 2345.86   617.5  2346.9   626.2 2345.21   639.4 2344.77   659.4 2342.98
   665.6 2341.93   671.5 2341.69   683.1 2341.88   684.6    2343   687.5 2346.29
   691.9 2354.36   695.7 2359.58     705 2368.78   714.1 2375.37   744.4 2404.27
     762 2419.18   771.4 2428.43   780.5 2436.71   792.7 2446.92   805.5  2458.5
#Mann= 6 ,-1,0
       0     .05       0     352     .06       0     462     .05       0
     572      .1       0   659.4    .045       0   684.6      .1       0
Bank Sta=659.4,684.6
XS Rating Curve= 0 ,0
Exp/Cntr=0.3,0.1

Type RM Length L Ch R = 1 ,1465    ,145.5,147.5,149.8
XS GIS Cut Line= 4
2255033.23600047389579.809191057 2254838.9262747389378.302808777
2254596.63883886388994.4811282422254531.53248658388987.544870754
#Sta/Elev= 30
       0 2362.05    75.9 2361.28   107.3 2363.13   158.2 2359.53     178 2357.27
   203.7 2352.55     237 2349.44   371.1 2346.88   390.2 2345.67   413.2 2342.61
   459.6  2343.1   470.5 2341.59   494.9 2341.43   509.9 2339.83   524.9 2340.66
  528.76 2341.74   536.7 2345.24   541.4 2345.97   645.5 2343.51   683.3 2344.34
   697.5 2343.84   725.9 2345.33   738.3 2346.88   750.4 2346.95   754.4 2347.89
   758.4 2350.92   762.5 2354.88   774.5 2368.49   790.6 2381.36799.3021 2386.57
#Mann= 7 ,-1,0
       0     .06       0     100     .05       0  399.93      .1       0
   494.9    .045       0  528.76      .1       0  629.93     .05       0
  763.83      .1       0
#XS Ineff= 2 , 0
                          541.89         2361.68
Permanent Ineff=
       F       F
Bank Sta=494.9,528.76
XS Rating Curve= 0 ,0
Exp/Cntr(USF)=0,0
Exp/Cntr=0.5,0.3

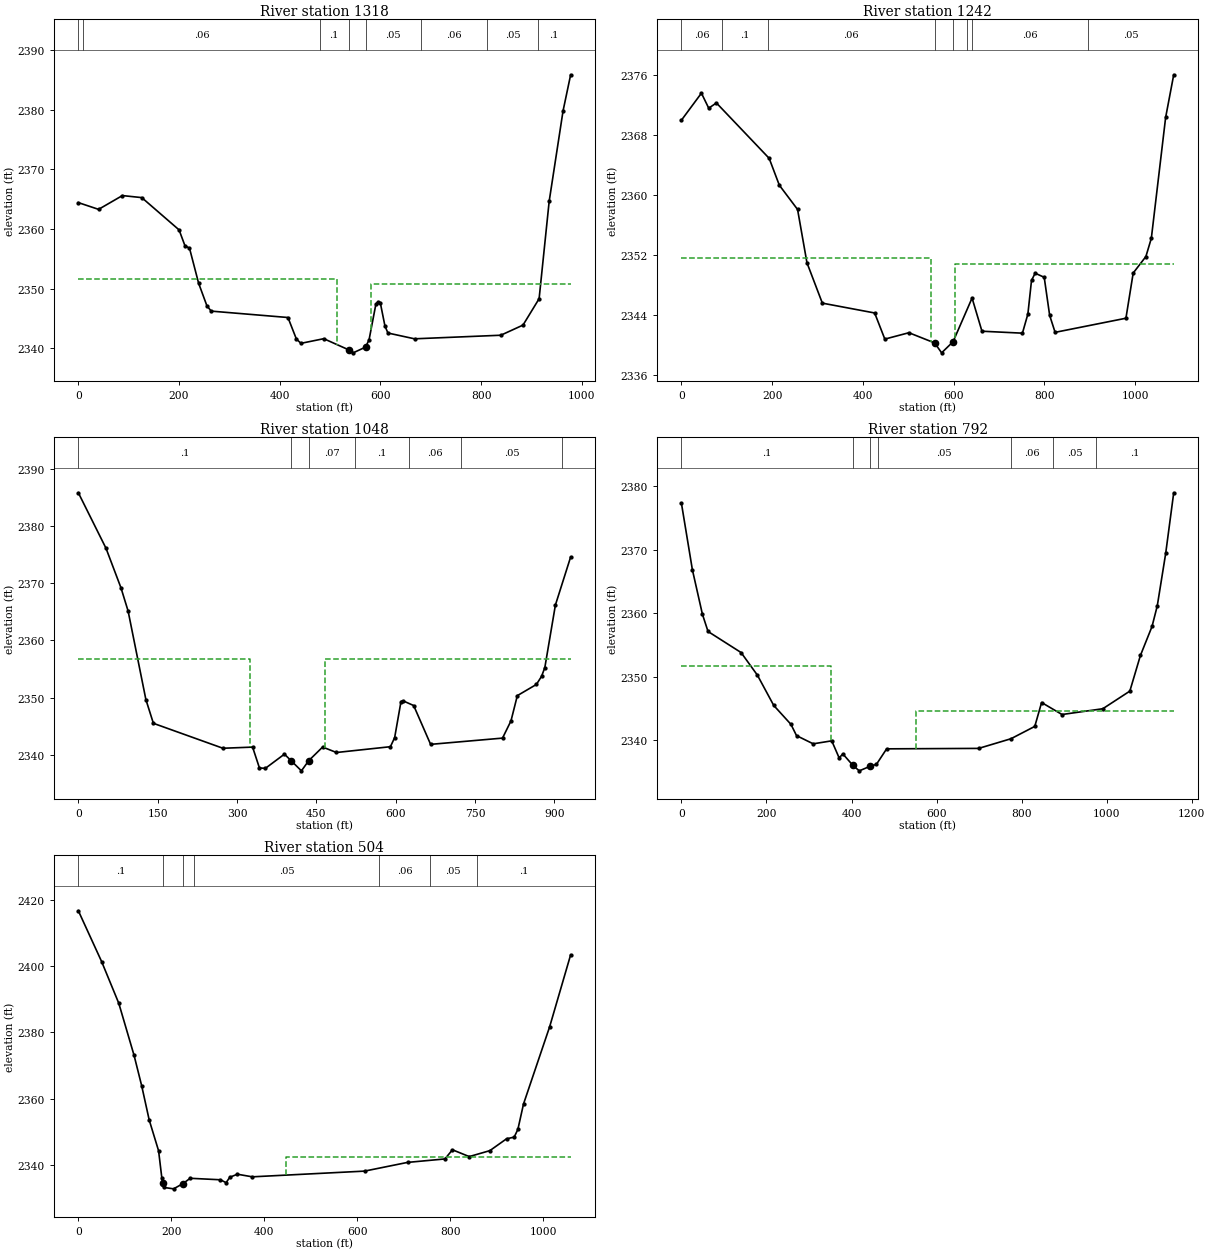
Type RM Length L Ch R = 1 ,1318    ,76.1,76.1,78.8
XS GIS Cut Line= 3
2255090.60194146389584.8142731572254750.75982849388935.782473087
2254505.54042148388929.118902244
#Sta/Elev= 30
       0 2364.44    40.2 2363.31    87.5 2365.62     126 2365.28   200.1 2359.87
   211.8 2357.21   220.8 2356.81   238.9 2350.94   255.3 2347.17   263.9 2346.26
   416.4 2345.19     433 2341.61   442.1 2340.86   487.5 2341.64   536.9 2339.78
   545.9 2339.27   570.5 2340.23   577.5 2341.45   591.1 2347.44   595.6 2347.83
   600.1 2347.54   609.1 2343.75     615 2342.59   667.8 2341.62   839.2 2342.22
   883.3 2343.92   915.3 2348.34   935.3 2364.67   962.9 2379.83977.9319 2385.86
#Mann= 8 ,-1,0
       0     .05       0      10     .06       0     480      .1       0
   536.9    .045       0   570.5     .05       0     680     .06       0
  812.62     .05       0  912.62      .1       0
#XS Ineff= 2 , 0
          514.15  2351.6  581.13          2350.8
Permanent Ineff=
       F       F
Bank Sta=536.9,570.5
XS Rating Curve= 0 ,0
Exp/Cntr(USF)=0,0
Exp/Cntr=0.5,0.3

Type RM Length L Ch R = 1 ,1242    ,220.8,193.4,161.4
XS GIS Cut Line= 3
2255151.90679321389562.1581322922254818.72825108388895.801048031
2254478.88613811388885.139334683
#Sta/Elev= 30
       0    2370    44.1  2373.6    60.2  2371.6    77.1  2372.3   193.4 2364.92
   215.8 2361.34     256 2358.11   276.7 2351.01   310.6 2345.63   425.9 2344.32
   448.3 2340.84   501.4 2341.69   558.1 2340.33   573.5 2339.01   598.7 2340.49
   640.6 2346.31   662.4 2341.89   751.6 2341.63   763.6 2344.18   771.6 2348.65
   779.6 2349.62   799.6 2349.07   811.6    2344   823.6 2341.74   979.7 2343.62
   995.7 2349.64  1023.7 2351.84  1035.7 2354.27  1067.2 2370.361085.019 2376.05
#Mann= 8 ,-1,0
       0     .06       0      90      .1       0     190     .06       0
   558.1    .045       0   598.7     .06       0     630     .05       0
     640     .06       0  895.01     .05       0
#XS Ineff= 2 , 0
          550.18  2351.6  602.07          2350.8
Permanent Ineff=
       F       F
Bank Sta=558.1,598.7
XS Rating Curve= 0 ,0
Exp/Cntr(USF)=0,0
Exp/Cntr=0.5,0.3

Type RM Length L Ch R = 1 ,1048    ,240.7,256.5,263.9
XS GIS Cut Line= 4
2255352.53857884389026.3957088432255145.92166569388897.487018821
2254865.74290841388876.3257796012254459.34981382388875.196894605
#Sta/Elev= 30
       0 2385.77    52.3 2376.09    80.6 2369.19    94.1 2365.14   127.7  2349.7
   141.9 2345.55   273.4  2341.2   329.5  2341.4   342.4 2337.77   353.6 2337.69
   389.7 2340.17   402.1 2339.05   421.8 2337.26   435.7 2339.04   461.9 2341.41
   488.1 2340.46   590.1 2341.47   598.1 2343.05   610.1 2349.35   614.1 2349.47
   634.1 2348.65   666.1 2341.88   802.1 2342.97   818.1 2345.98   830.1 2350.38
   866.1 2352.33   875.9 2353.74   882.1 2355.28   902.1 2366.19   930.9 2374.57
#Mann= 7 ,-1,0
       0      .1       0   402.1    .045       0   435.7     .07       0
  523.53      .1       0  624.51     .06       0  724.51     .05       0
  914.51     .06       0
#XS Ineff= 2 , 0
          324.87 2356.82  466.17         2356.71
Permanent Ineff=
       F       F
Bank Sta=402.1,435.7
XS Rating Curve= 0 ,0
Exp/Cntr=0.3,0.1

Type RM Length L Ch R = 1 ,792     ,301.7,288.3,264.8
XS GIS Cut Line= 4
 2255359.1756584388866.701206947 2255225.4958754388743.140629715
2254828.86211481388571.2437331682254285.52031183388572.997865343
#Sta/Elev= 30
       0 2377.29    25.8 2366.82    49.4 2359.82    62.6 2357.11   140.3  2353.8
   178.7 2350.24   217.1 2345.48   257.6  2342.5   270.7 2340.73   309.9 2339.44
   353.5 2339.91   370.9 2337.23   379.7 2337.85   403.5 2336.03   418.3 2335.19
   443.32335.897   458.6 2336.21   482.6 2338.65     699 2338.72     775 2340.24
     831 2342.18     847 2345.94     895 2344.05     991 2344.96  1054.5 2347.73
  1079.4 2353.34  1106.7  2357.9    1119 2361.13  1138.8 2369.38  1157.7 2378.93
#Mann= 7 ,-1,0
       0      .1       0   403.5    .045       0   443.3      .1       0
  462.04     .05       0  774.32     .06       0  874.32     .05       0
  974.32      .1       0
#XS Ineff= 2 , 0
          350.94 2351.73  552.07         2344.64
Permanent Ineff=
       F       F
Bank Sta=403.5,443.3
XS Rating Curve= 0 ,0
Exp/Cntr=0.3,0.1

Type RM Length L Ch R = 1 ,504     ,275.5,275,255.4
XS GIS Cut Line= 4
2255308.96489519 388420.19154735 2255173.1726762388388.985195009
2254937.79353823388419.1291947972254285.57070219 388563.04957259
#Sta/Elev= 30
       0 2416.61    50.1 2401.29      87 2388.73   119.8 2373.07   136.3 2363.84
   152.4 2353.57   172.6 2344.29   179.7 2335.96   181.9 2334.48   184.7 2333.22
   204.9 2332.81     225 2334.38   240.5 2335.99   305.7 2335.54   317.8 2334.67
   325.8 2336.29     342 2337.22   374.2 2336.43   615.6 2338.15   708.2 2340.78
   788.6 2341.82   804.7 2344.58   840.9 2342.53   885.2 2344.32   921.1 2347.89
   937.5 2348.39   945.5 2350.73   957.6 2358.37  1013.9 2381.681059.006 2403.34
#Mann= 7 ,-1,0
       0      .1       0   181.9    .045       0     225      .1       0
  249.33     .05       0  646.63     .06       0  756.63     .05       0
  856.63      .1       0
#XS Ineff= 2 , 0
                          447.66         2342.29
Permanent Ineff=
       F       F
Bank Sta=181.9,225
XS Rating Curve= 0 ,0
Exp/Cntr(USF)=0,0
Exp/Cntr=0.3,0.1