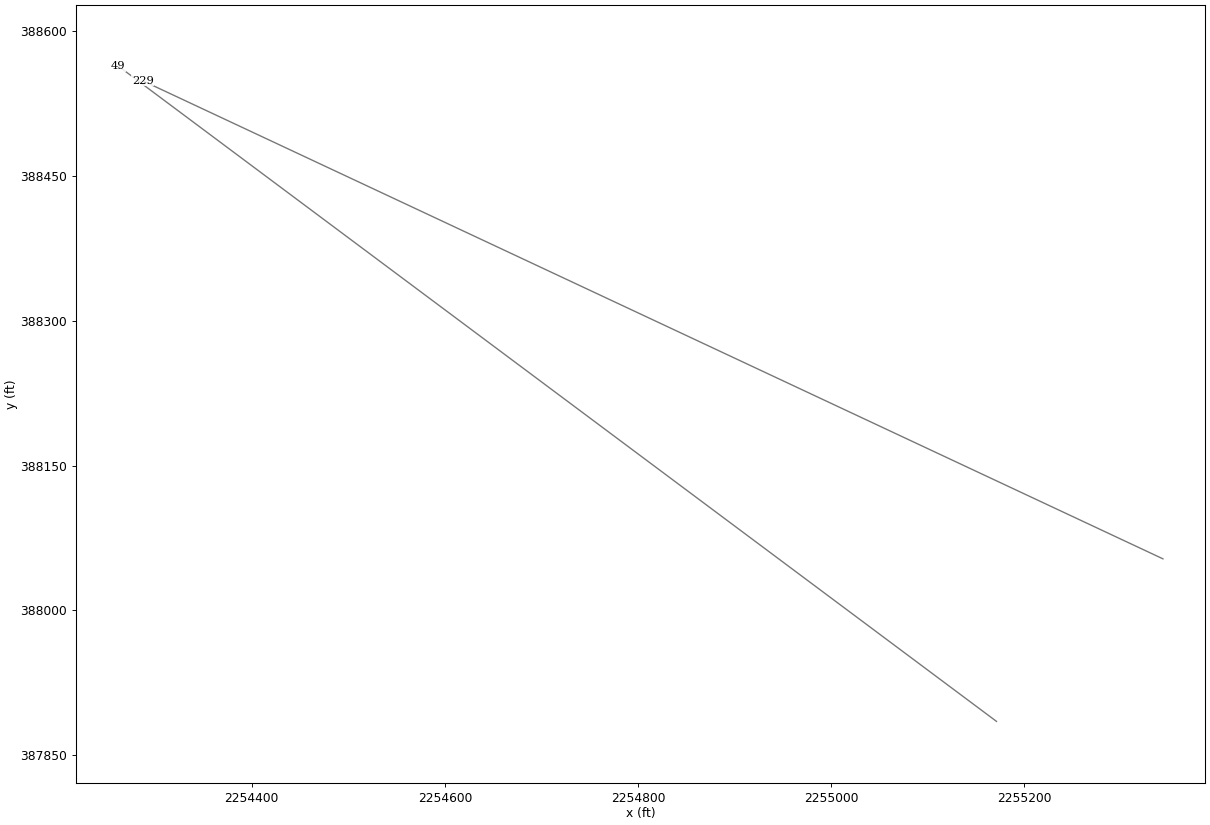
HEC-RAS study ANTHNYCK.prj: ANTHNYCK

--- ANTHNYCK.g01 (geometry) --- (continued)

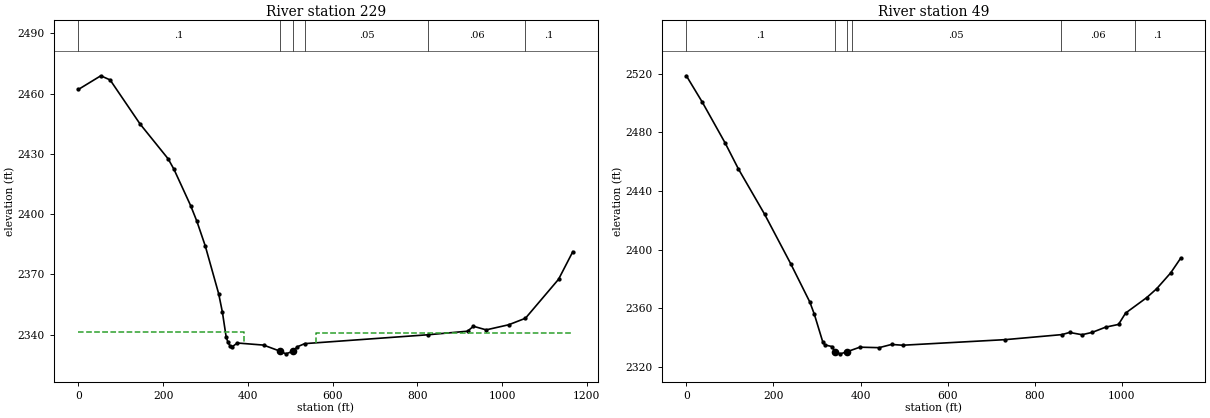
Type RM Length L Ch R = 1 ,229     ,183.2,180,172.5
XS GIS Cut Line= 2
2255343.95086084388053.4557225782254287.04674537388548.727788937
#Sta/Elev= 30
       0 2462.08    52.8 2468.86    74.8 2466.79   145.5 2444.87   211.8 2427.54
   225.6  2422.3   264.8 2404.31   279.4  2396.6   299.4 2384.22   331.1 2360.41
   339.9 2351.23   348.7 2338.99   353.1 2336.17   357.6 2334.62   363.6 2334.13
   375.2  2335.9   437.1 2334.86   474.9 2331.92   489.9 2330.51   507.2 2331.86
   516.6    2334   534.3 2335.59   825.8 2340.01   918.6 2341.77   932.6 2344.22
   962.7 2342.44  1015.8 2344.97  1055.4 2348.21  1133.6 2367.61  1167.2 2381.33
#Mann= 6 ,-1,0
       0      .1       0   474.9    .045       0   507.2      .1       0
   534.3     .05       0   825.8     .06       0  1055.4      .1       0
#XS Ineff= 2 , 0
          390.59 2341.34   560.4         2340.81
Permanent Ineff=
       F       F
Bank Sta=474.9,507.2
XS Rating Curve= 0 ,0
Exp/Cntr(USF)=0,0
Exp/Cntr=0.3,0.1

Type RM Length L Ch R = 1 ,49      ,,,
XS GIS Cut Line= 2
2255171.49383263 387885.060578482254261.77189881388563.880086973
#Sta/Elev= 30
       0 2518.56    36.8 2500.48      89 2472.78   119.6 2455.02   179.7 2424.17
   239.7  2390.4   283.6 2364.28     294 2355.87   313.6 2336.79   318.6 2335.08
   334.6 2333.98   341.3 2330.42   353.5 2329.03   368.3  2330.4   398.4 2333.57
   442.6 2333.24   471.2 2335.43   496.9  2334.9   732.8 2338.72   862.6 2342.15
   879.9 2343.61   908.5 2342.07   931.4 2343.61   962.8 2347.23   992.3 2349.08
  1008.5  2356.8    1057 2367.34    1080 2373.43  1112.1 2384.21  1135.1 2394.25
#Mann= 6 ,-1,0
       0      .1       0   341.3    .045       0   368.3      .1       0
     380     .05       0     860     .06       0    1030      .1       0
Bank Sta=341.3,368.3
XS Rating Curve= 0 ,0
Exp/Cntr(USF)=0,0
Exp/Cntr=0.3,0.1
LCMann Table=0

Chan Stop Cuts=-1
Use User Specified Reach Order=0
Composite Channel Slope=5